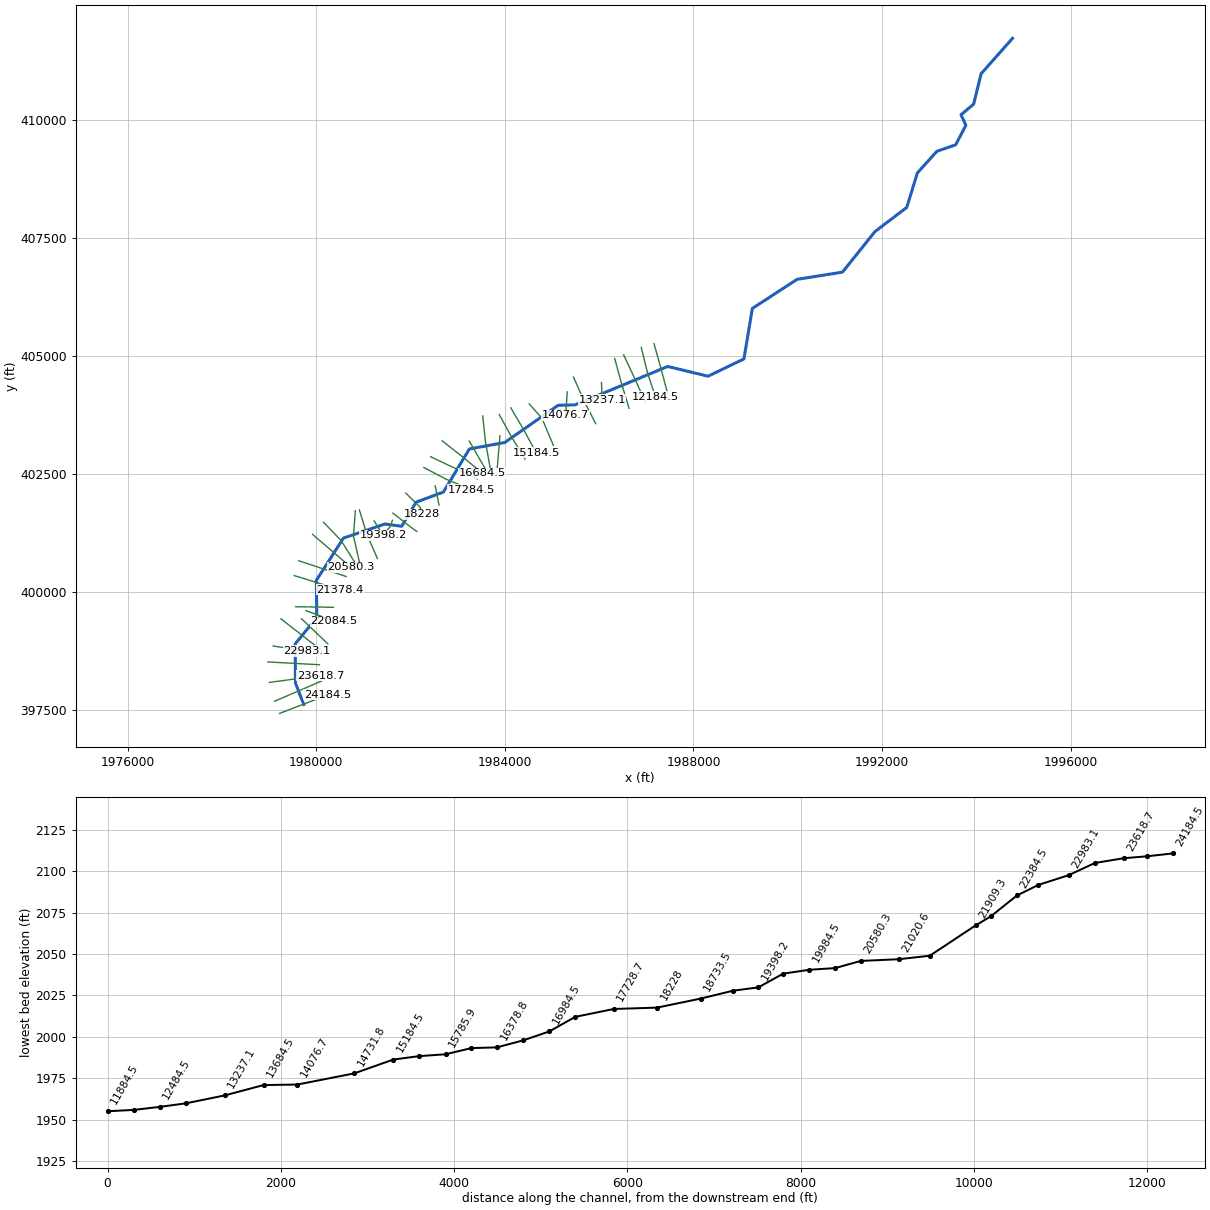
--- LaurelCrk4.prj (project) ---

Proj Title=LaurelCrk4
Current Plan=p01
Default Exp/Contr=0,0
English Units
Geom File=g01
Flow File=f01
Plan File=p01
BEGIN DESCRIPTION:
END DESCRIPTION:
DSS Export Rating Curves= 0
DSS Export Rating Curve Sorted= 0
DSS Export Volume Flow Curves= 0
DXF OffsetX= 0
DXF OffsetY= 0
DXF ScaleX= 0
DXF ScaleY= 0

--- LaurelCrk4.p01 (plan) ---

Plan Title=Floodplain
Program Version=4.00
Geom File=g01
Flow File=f01
K Sum by GR=0
Std Step Tol=0.01
Critical Tol=0.01
Num of Std Step Trials=20
Max Error Tol=0.3
Flow Tol Ratio=0.001
Split Flow NTrial=30
Split Flow Tol=0.02
Split Flow Ratio=0.02
Log Output Level=0
Friction Slope Method=1
Unsteady Friction Slope Method=2
Unsteady Bridges Friction Slope Method=1
Global Log Level=0
CheckData=False
Run HTab=0
Run UNet=0
Run PostProcess=0
UNET Theta=0
UNET Theta Warmup=0
UNET ZTol=0
UNET ZSATol=0
UNET MxIter=0
UNET MaxInSteps=0
UNET DtIC=0
UNET DtMin=0
UNET MaxCRTS=0
UNET WFStab=0
UNET SFStab=0
UNET WFX=0
UNET SFX=0
UNET DSS MLevel=0
UNET DZMax Abort=0
UNET Convert EG Bridges=0
UNET Use Existing IB Tables=0
UNET Froude Limit=0
UNET Froude Power=0
Write IC File=0
Echo Input=False
Echo Output=False
Write Detailed=0

--- LaurelCrk4.f01 (steady flow) ---

Flow Title=NFF Regression Equation
Program Version=4.10
Number of Profiles= 1
Profile Names=P100yr
River Rch & RM=LaurelCrk4,Main            ,24184.5
 529.378
River Rch & RM=LaurelCrk4,Main            ,21378.4
566.9891
River Rch & RM=LaurelCrk4,Main            ,21020.6
747.5062
River Rch & RM=LaurelCrk4,Main            ,18733.5
     809
River Rch & RM=LaurelCrk4,Main            ,18228
   927.8
River Rch & RM=LaurelCrk4,Main            ,16378.8
965.0743
River Rch & RM=LaurelCrk4,Main            ,16084.5
1112.107
River Rch & RM=LaurelCrk4,Main            ,9983.8
2068.529
River Rch & RM=LaurelCrk4,Main            ,6484.5
2470.999
River Rch & RM=LaurelCrk4,Main            ,186.5
2546.636
Boundary for River Rch & Prof#=LaurelCrk4,Main            , 1
Up Type= 0
Dn Type= 3
Dn Slope=0.028666
DSS Import GetInterval= 0
DSS Import GetPeak= 0
DSS Import FillOption= 0

--- LaurelCrk4.g01 (geometry) ---

Geom Title=USGS 3m DEM
Program Version=4.00

River Reach=LaurelCrk4     ,Main
Reach XY= 30
     1979736.292      397614.418     1979559.209      398071.016
     1979551.697      398897.852     1980012.334      399459.905
     1980001.484      400245.496     1980576.570      401142.196
     1981458.514      401440.807     1981812.681      401392.196
     1982116.500      401902.613     1982696.361      402117.891
     1983248.445      403031.085     1983994.973      403166.502
     1985130.389      403956.432     1985488.028      403965.113
     1987453.149      404779.184     1988308.505      404572.123
     1989069.625      404939.071     1989248.445      406008.516
     1990196.361      406624.835     1991160.455      406777.965
     1991847.659      407636.092     1992522.750      408149.141
     1992748.445      408880.044     1993161.639      409338.377
     1993560.945      409475.530     1993776.223      409890.460
     1993673.792      410112.682     1993941.153      410338.377
     1994099.139      410980.738     1994765.271      411732.069

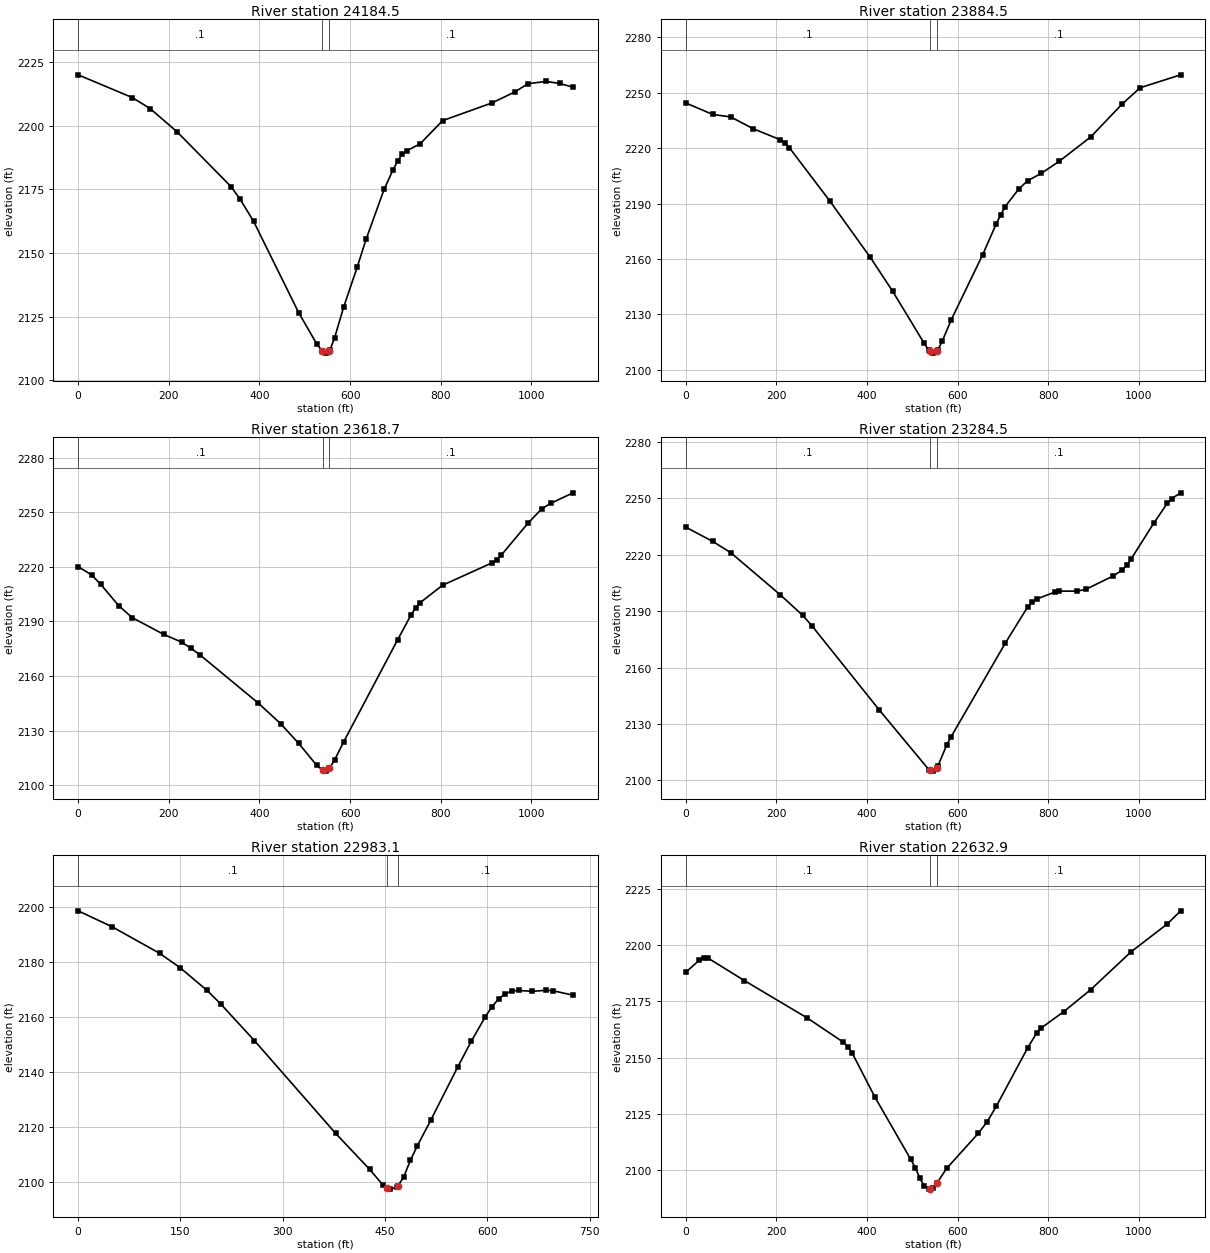
Type RM Length L Ch R = 1 ,24184.5,299.1,300,300.9
XS GIS Cut Line= 3
     1979223.095      397427.750     1979732.702      397623.752
     1980242.309      397819.754
#Sta/Elev= 30
       0 2220.05   119.1 2211.14   158.8 2206.80   218.4 2197.64   337.5 2176.10
   357.4 2171.17   387.2 2162.46   486.4 2126.66   526.2 2114.39   538.5 2111.57
   546.0 2110.71   553.5 2111.73   555.9 2112.06   565.8 2116.72   585.7 2128.71
   615.5 2144.39   635.4 2155.47   675.0 2175.01   694.9 2182.77   704.8 2186.14
   714.8 2188.77   724.7 2190.20   754.5 2192.92   804.1 2202.05   913.3 2209.03
   963.0 2213.28   992.7 2216.56  1032.4 2217.46  1062.2 2216.67  1092.0 2215.17
#Mann= 3 , 0 , 0
       0     0.1       0   538.5   0.045       0   553.5     0.1       0
Bank Sta=   538.5,   553.5
Exp/Cntr=0.3,0.1

Type RM Length L Ch R = 1 ,23884.5,272,265.8,259.6
XS GIS Cut Line= 3
     1979122.246      397686.653     1979623.508      397903.107
     1980124.953      398119.137
#Sta/Elev= 30
       0 2244.50    59.6 2238.27    99.3 2236.93   148.9 2230.53   208.5 2224.59
   218.4 2223.02   228.3 2220.35   317.7 2191.42   407.0 2160.90   456.6 2142.44
   526.2 2114.20   536.1 2110.49   538.5 2110.12   546.0 2108.96   553.5 2110.11
   555.9 2110.48   565.8 2115.41   585.7 2126.99   655.2 2162.32   685.0 2178.97
   694.9 2183.91   704.8 2188.38   734.6 2197.83   754.5 2202.42   784.2 2206.30
   824.0 2212.88   893.4 2226.08   963.0 2243.96  1002.6 2252.75  1092.0 2259.75
#Mann= 3 , 0 , 0
       0     0.1       0   538.5   0.045       0   553.5     0.1       0
Bank Sta=   538.5,   553.5
Exp/Cntr=0.3,0.1

Type RM Length L Ch R = 1 ,23618.7,338.4,334.2,330
XS GIS Cut Line= 3
     1979005.477      398083.551     1979546.650      398155.991
     1980087.823      398228.432
#Sta/Elev= 30
       0 2220.14    29.8 2215.53    49.6 2210.43    89.4 2198.72   119.1 2192.13
   188.6 2182.93   228.3 2178.66   248.2 2175.42   268.0 2171.82   397.1 2145.24
   446.7 2133.87   486.4 2123.12   526.2 2111.04   539.3 2108.34   546.0 2107.81
   554.3 2109.31   565.8 2113.92   585.7 2123.83   704.8 2179.91   734.6 2193.64
   744.6 2197.55   754.5 2200.32   804.1 2209.91   913.3 2222.21   923.2 2223.83
   933.2 2226.31   992.7 2244.04  1022.5 2251.76  1042.4 2254.86  1092.0 2260.66
#Mann= 3 , 0 , 0
       0     0.1       0   539.3   0.045       0   554.3     0.1       0
Bank Sta=   539.3,   554.3
Exp/Cntr=0.3,0.1

Type RM Length L Ch R = 1 ,23284.5,303.4,301.4,299.4
XS GIS Cut Line= 3
     1978975.877      398517.523     1979521.081      398488.053
     1980066.285      398458.584
#Sta/Elev= 30
       0 2234.73    59.6 2227.10    99.3 2221.15   208.5 2198.74   258.1 2187.78
   278.0 2182.36   426.9 2137.49   536.1 2105.78   538.5 2105.57   546.0 2104.93
   553.5 2106.82   555.9 2107.43   575.8 2118.85   585.7 2123.31   704.8 2172.93
   754.5 2192.35   764.4 2195.00   774.3 2196.48   814.0 2200.16   824.0 2200.71
   863.7 2200.68   883.5 2201.72   943.1 2208.77   963.0 2211.87   972.9 2214.47
   982.8 2217.84  1032.4 2236.76  1062.2 2247.33  1072.2 2249.92  1092.0 2252.99
#Mann= 3 , 0 , 0
       0     0.1       0   538.5   0.045       0   553.5     0.1       0
Bank Sta=   538.5,   553.5
Exp/Cntr=0.3,0.1

Type RM Length L Ch R = 1 ,22983.1,361.9,350.2,338.4
XS GIS Cut Line= 2
     1979087.538      398854.474     1979805.538      398750.553
#Sta/Elev= 30
       0 2198.77    49.7 2192.98   119.3 2183.34   149.1 2178.16   188.8 2169.87
   208.7 2164.98   258.4 2151.58   377.6 2117.82   427.3 2104.78   447.2 2098.95
   453.2 2098.13   457.2 2097.59   467.1 2098.20   468.2 2098.61   477.0 2101.88
   487.0 2108.02   496.9 2113.18   516.8 2122.61   556.5 2142.03   576.4 2151.39
   596.3 2160.02   606.2 2163.77   616.2 2166.69   626.1 2168.63   636.0 2169.64
   646.0 2169.81   665.8 2169.50   685.7 2169.87   695.7 2169.72   725.5 2168.11
#Mann= 3 , 0 , 0
       0     0.1       0   453.2   0.045       0   468.2     0.1       0
Bank Sta=   453.2,   468.2
Exp/Cntr=0.3,0.1

Type RM Length L Ch R = 1 ,22632.9,250.6,248.3,246.1
XS GIS Cut Line= 2
     1979251.442      399431.178     1980113.344      398760.318
#Sta/Elev= 30
       0 2187.85    29.8 2193.22    39.7 2194.24    49.6 2194.10   129.1 2184.21
   268.1 2167.60   347.5 2156.90   357.4 2154.90   367.4 2152.01   417.0 2132.67
   496.5 2104.90   506.4 2101.28   516.3 2096.70   526.2 2093.07   536.2 2091.71
   538.8 2091.86   546.1 2092.27   553.8 2094.21   575.9 2100.94   645.4 2116.41
   665.3 2121.61   685.1 2128.36   754.6 2154.39   774.5 2160.96   784.4 2163.16
   834.0 2170.38   893.6 2180.16   983.0 2196.99  1062.4 2209.26  1092.2 2215.12
#Mann= 3 , 0 , 0
       0     0.1       0   538.8   0.045       0   553.8     0.1       0
Bank Sta=   538.8,   553.8
Exp/Cntr=0.3,0.1

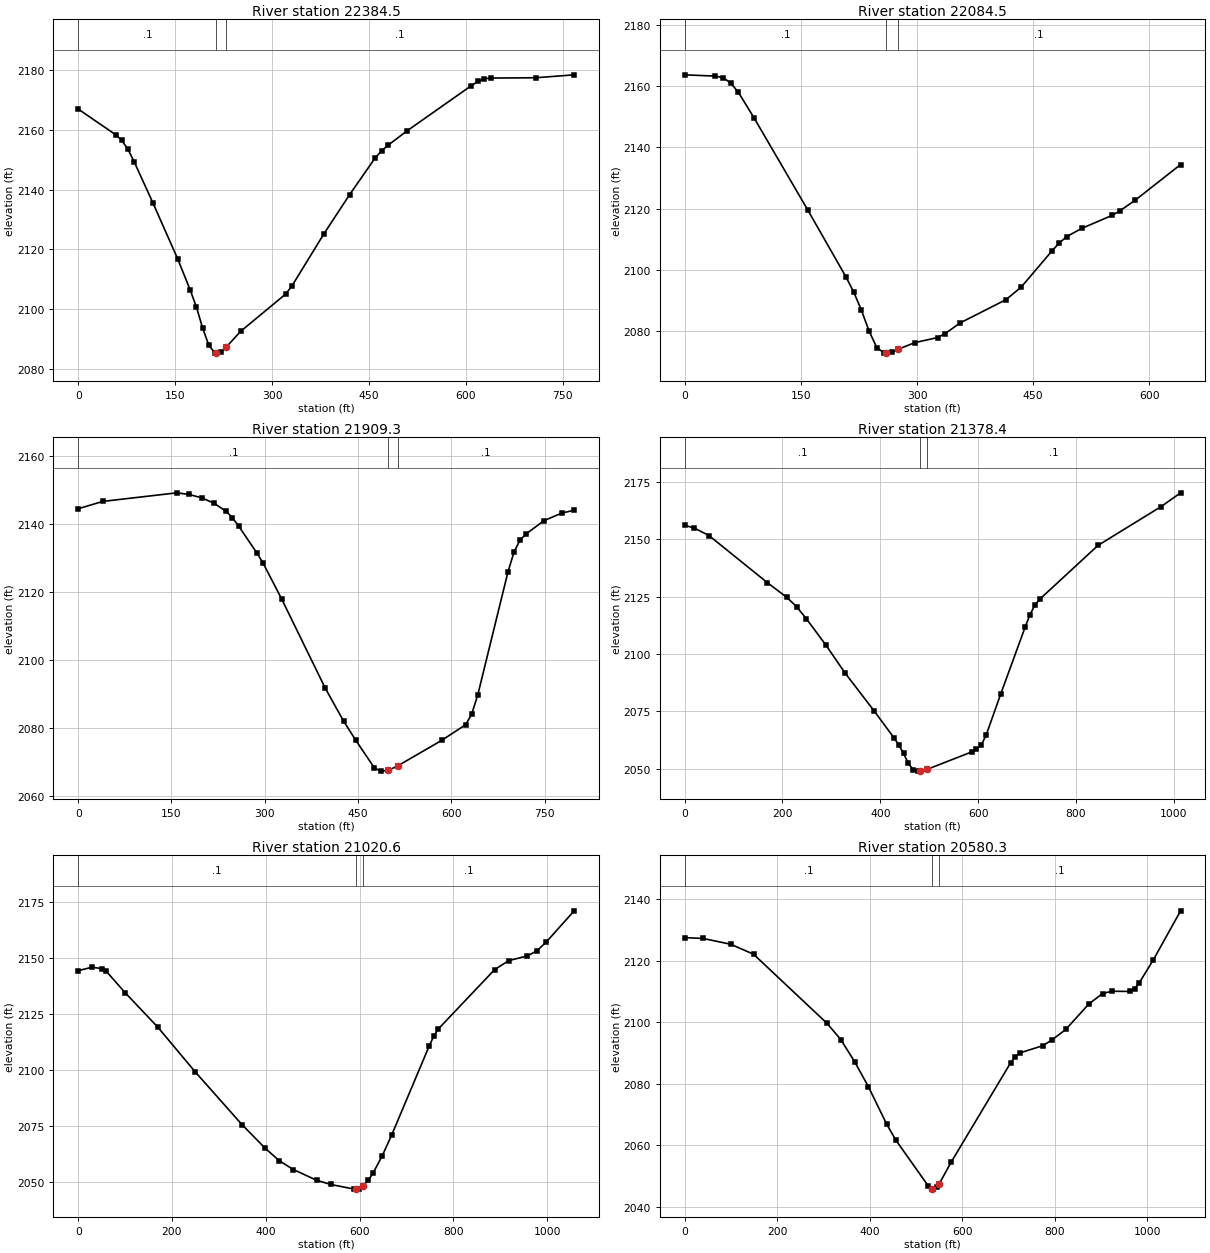
Type RM Length L Ch R = 1 ,22384.5,291,300,309
XS GIS Cut Line= 3
     1979689.172      399431.583     1979849.558      399278.834
     1980244.937      398902.282
#Sta/Elev= 30
       0 2166.94    57.8 2158.38    67.4 2156.48    77.0 2153.46    86.7 2149.26
   115.6 2135.56   154.1 2116.76   173.3 2106.43   183.0 2100.68   192.6 2093.66
   202.2 2087.90   211.9 2085.31     214 2085.39   221.5 2085.68     229 2087.31
   251.3 2092.58   320.8 2105.02   330.7 2107.77   380.3 2125.23   420.0 2138.31
   459.7 2150.64   469.7 2153.01   479.6 2154.86   509.4 2159.73   608.6 2174.80
   618.6 2176.19   628.5 2177.08   638.4 2177.31   707.9 2177.41   767.5 2178.39
#Mann= 3 , 0 , 0
       0     0.1       0     214   0.045       0     229     0.1       0
Bank Sta=     214,     229
Exp/Cntr=0.3,0.1

Type RM Length L Ch R = 1 ,22084.5,167.2,175.1,183
XS GIS Cut Line= 3
     1979782.864      399606.485     1980033.060      399511.028
     1980381.828      399379.748
#Sta/Elev= 30
       0 2163.66    39.7 2163.24    49.6 2162.72    59.5 2160.98    69.4 2157.92
    89.3 2149.72   158.7 2119.62   208.3 2097.64   218.2 2092.77   228.1 2086.86
   238.0 2080.04   248.0 2074.60   257.9 2072.77   260.3 2072.85   267.8 2073.10
   275.3 2074.00   297.2 2076.20   326.6 2077.86   336.4 2079.17   356.0 2082.68
   414.9 2090.23   434.5 2094.32   473.7 2105.98   483.5 2108.69   493.3 2110.83
   513.0 2113.54   552.2 2117.79   562.0 2119.25   581.6 2122.68   640.4 2134.37
#Mann= 3 , 0 , 0
       0     0.1       0   260.3   0.045       0   275.3     0.1       0
Bank Sta=   260.3,   275.3
Exp/Cntr=0.3,0.1

Type RM Length L Ch R = 1 ,21909.3,538.1,530.8,522.9
XS GIS Cut Line= 3
     1979565.575      399687.732     1980111.168      399680.812
     1980362.933      399674.506
#Sta/Elev= 30
       0 2144.52    39.7 2146.68   158.7 2149.20   178.6 2148.71   198.4 2147.73
   218.2 2146.16   238.1 2143.73   248.0 2141.87   257.9 2139.44   287.7 2131.41
   297.6 2128.41   327.4 2117.87   396.8 2091.88   426.6 2082.07   446.4 2076.36
   476.2 2068.28   486.1 2067.31   498.9 2067.52   513.9 2068.87   584.4 2076.35
   623.1 2080.98   632.8 2084.11   642.5 2089.73   690.9 2125.80   700.6 2131.69
   710.3 2135.25   720.0 2137.08   749.0 2141.01   778.1 2143.28   797.5 2144.07
#Mann= 3 , 0 , 0
       0     0.1       0   498.9   0.045       0   513.9     0.1       0
Bank Sta=   498.9,   513.9
Exp/Cntr=0.3,0.1

Type RM Length L Ch R = 1 ,21378.4,357.6,357.8,358.6
XS GIS Cut Line= 2
     1979533.454      400347.159     1980502.754      400048.622
#Sta/Elev= 30
       0 2156.14    19.9 2154.92    49.7 2151.67   169.0 2131.15   208.8 2124.71
   228.7 2120.70   248.6 2115.45   288.4 2104.02   328.1 2091.69   387.8 2075.10
   427.6 2063.58   437.5 2060.47   447.5 2056.72   457.4 2052.27   467.3 2049.56
   477.3 2048.94   481.4 2049.03   496.4 2049.76   586.7 2057.29   596.6 2058.40
   606.6 2060.39   616.5 2064.66   646.3 2082.57   696.0 2111.59   706.0 2117.11
   715.9 2121.24   725.9 2123.87   845.2 2147.36   974.5 2164.33  1014.2 2170.30
#Mann= 3 , 0 , 0
       0     0.1       0   481.4   0.045       0   496.4     0.1       0
Bank Sta=   481.4,   496.4
Exp/Cntr=0.3,0.1

Type RM Length L Ch R = 1 ,21020.6,448.6,439.8,430.9
XS GIS Cut Line= 2
     1979631.176      400661.042     1980635.017      400328.264
#Sta/Elev= 30
       0 2144.18    29.9 2145.75    49.9 2145.09    59.9 2143.90    99.8 2134.43
   169.6 2119.04   249.4 2099.12   349.2 2075.61   399.1 2064.98   429.0 2059.47
   458.9 2055.57   508.8 2050.76   538.8 2048.92   588.6 2046.85   591.8 2046.90
   598.6 2047.00   606.8 2048.08   618.6 2050.84   628.6 2053.93   648.5 2061.76
   668.5 2070.96   748.3 2110.53   758.2 2115.02   768.2 2118.28   888.0 2144.65
   917.9 2148.65   957.8 2150.78   977.8 2152.95   997.7 2156.84  1057.6 2170.85
#Mann= 3 , 0 , 0
       0     0.1       0   591.8   0.045       0   606.8     0.1       0
Bank Sta=   591.8,   606.8
Exp/Cntr=0.3,0.1

Type RM Length L Ch R = 1 ,20580.3,297.9,295.8,289
XS GIS Cut Line= 2
     1979922.597      401220.164     1980737.049      400522.880
#Sta/Elev= 30
       0 2127.53    39.7 2127.26    99.3 2125.39   148.9 2122.14   307.8 2099.67
   337.5 2094.41   367.3 2087.25   397.1 2079.12   436.8 2066.89   456.7 2061.70
   526.2 2046.94   534.7 2045.97   536.1 2045.81   546.0 2046.49   549.7 2047.35
   575.8 2054.50   704.8 2086.89   714.8 2088.88   724.7 2090.08   774.3 2092.42
   794.2 2094.31   824.0 2097.70   873.6 2105.95   903.4 2109.36   923.2 2110.11
   963.0 2110.04   972.9 2110.99   982.8 2112.86  1012.6 2120.16  1072.2 2136.24
#Mann= 3 , 0 , 0
       0     0.1       0   534.7   0.045       0   549.7     0.1       0
Bank Sta=   534.7,   549.7
Exp/Cntr=0.3,0.1

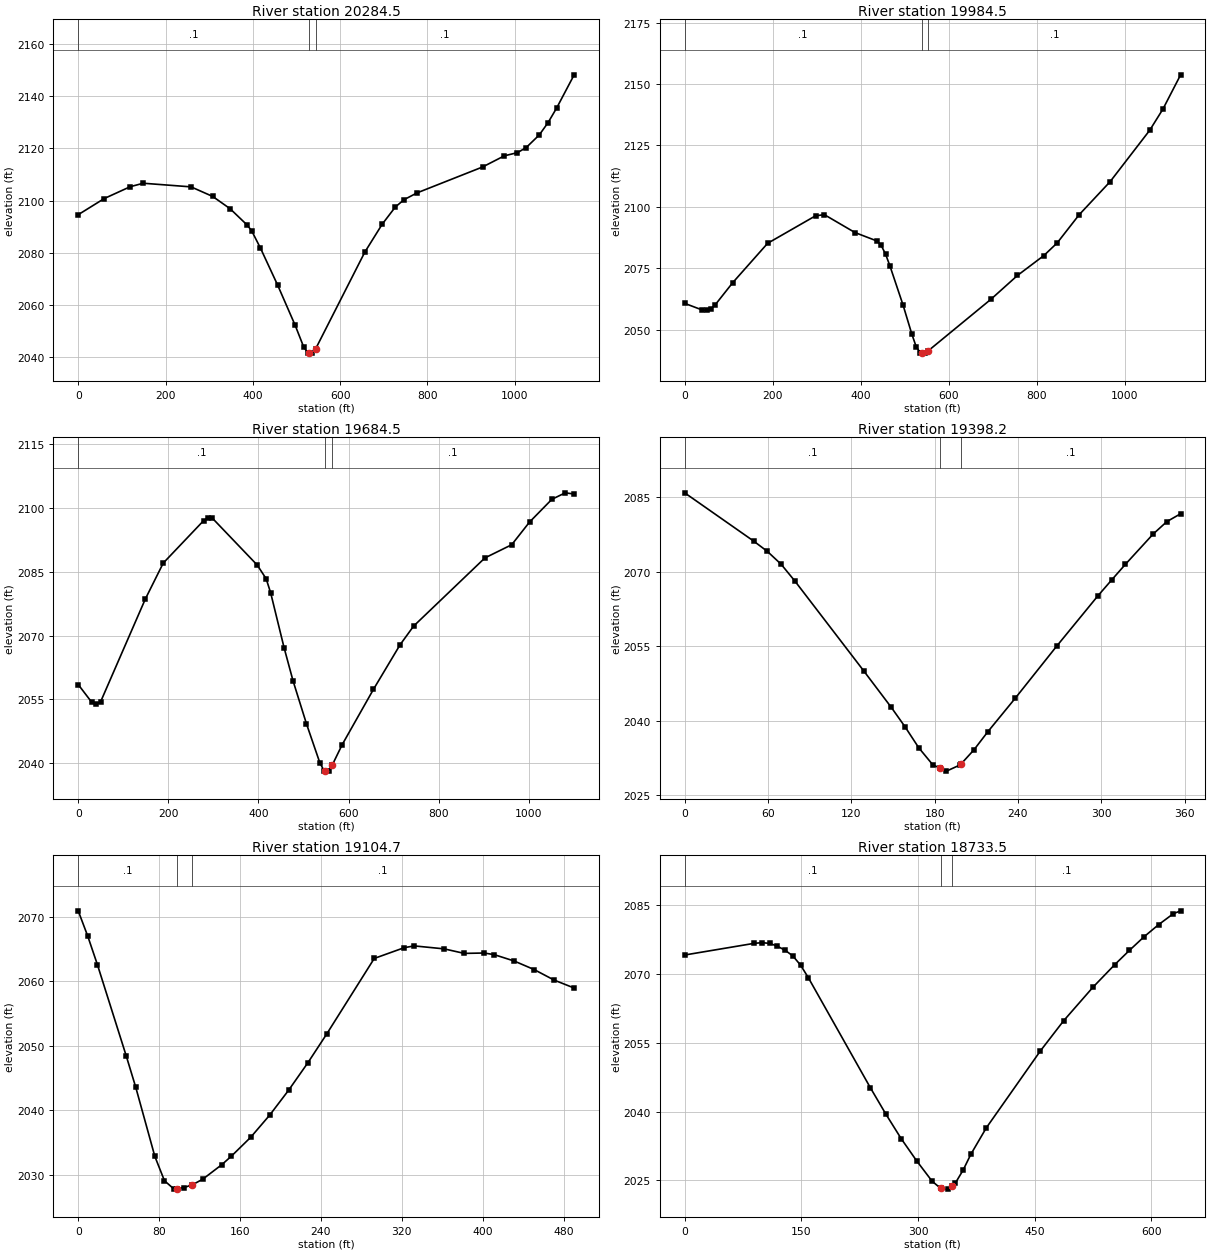
Type RM Length L Ch R = 1 ,20284.5,318.9,299.9,292.8
XS GIS Cut Line= 3
     1980153.555      401478.222     1980526.272      401092.196
     1980844.948      400584.651
#Sta/Elev= 30
       0 2094.56    59.6 2100.75   119.2 2105.30   149.0 2106.62   258.4 2105.23
   308.0 2101.56   347.8 2096.86   387.5 2090.51   397.5 2088.31   417.4 2081.76
   457.1 2067.44   496.8 2052.19   516.7 2043.73   526.7 2041.48   529.1 2041.49
   536.6 2041.52   544.1 2043.22   656.4 2080.20   696.4 2090.95   726.4 2097.52
   746.4 2100.33   776.3 2102.94   926.1 2112.85   976.1 2117.14  1006.0 2118.35
  1026.0 2120.29  1056.0 2125.14  1076.0 2129.83  1095.9 2135.49  1135.9 2148.19
#Mann= 3 , 0 , 0
       0     0.1       0   529.1   0.045       0   544.1     0.1       0
Bank Sta=   529.1,   544.1
Exp/Cntr=0.3,0.1

Type RM Length L Ch R = 1 ,19984.5,291.4,299.9,303.6
XS GIS Cut Line= 3
     1980828.668      401723.738     1980789.633      401179.679
     1980920.148      400613.690
#Sta/Elev= 30
       0 2060.73    39.7 2058.04    49.6 2057.85    59.5 2058.47    69.4 2060.16
   109.1 2069.15   188.4 2085.18   297.5 2096.40   317.4 2096.82   386.8 2089.55
   436.4 2086.14   446.3 2084.32   456.2 2080.78   466.1 2075.99   495.9 2060.06
   515.7 2048.32   525.6 2043.15   535.5 2040.47     538 2040.48   545.5 2040.50
     553 2041.40   695.7 2062.42   755.8 2072.09   815.8 2080.20   845.9 2085.32
   896.0 2096.83   966.1 2110.25  1056.2 2131.21  1086.2 2139.84  1126.3 2153.76
#Mann= 3 , 0 , 0
       0     0.1       0     538   0.045       0     553     0.1       0
Bank Sta=     538,     553
Exp/Cntr=0.3,0.1

Type RM Length L Ch R = 1 ,19684.5,280.9,286.4,289.5
XS GIS Cut Line= 3
     1980915.038      401739.028     1981077.996      401207.369
     1981297.666      400709.368
#Sta/Elev= 30
       0 2058.49    29.8 2054.35    39.7 2053.84    49.6 2054.41   149.0 2078.62
   188.7 2087.06   278.0 2097.01   288.0 2097.73   297.9 2097.59   397.2 2086.59
   417.0 2083.37   427.0 2080.06   456.8 2067.15   476.6 2059.38   506.4 2049.27
   536.2 2040.06   546.1 2038.12   548.6 2038.16   556.1 2038.26   563.6 2039.53
   585.8 2044.37   655.0 2057.34   714.4 2067.88   744.1 2072.22   902.4 2088.27
   961.8 2091.37  1001.4 2096.70  1050.9 2102.05  1080.6 2103.58  1100.4 2103.30
#Mann= 3 , 0 , 0
       0     0.1       0   548.6   0.045       0   563.6     0.1       0
Bank Sta=   548.6,   563.6
Exp/Cntr=0.3,0.1

Type RM Length L Ch R = 1 ,19398.2,313.4,293.3,273.3
XS GIS Cut Line= 2
     1981226.423      401509.185     1981413.481      401204.980
#Sta/Elev= 24
       0 2085.86    49.6 2076.16    59.5 2074.08    69.4 2071.50    79.4 2068.09
   129.0 2050.00   148.8 2042.67   158.7 2038.76   168.6 2034.53   178.6 2031.14
   184.2 2030.41   188.5 2029.85   198.4 2031.11   199.2 2031.35   208.3 2034.14
   218.2 2037.75   238.1 2044.55   267.8 2054.98   297.6 2065.15   307.5 2068.34
   317.4 2071.49   337.3 2077.56   347.2 2080.07   357.1 2081.65
#Mann= 3 , 0 , 0
       0     0.1       0   184.2   0.045       0   199.2     0.1       0
Bank Sta=   184.2,   199.2
Exp/Cntr=0.3,0.1

Type RM Length L Ch R = 1 ,19104.7,343,371.2,399.2
XS GIS Cut Line= 4
     1981615.655      401518.633     1981568.418      401384.480
     1981467.941      401272.281     1981554.982      401094.866
#Sta/Elev= 30
       0 2070.90     9.5 2066.95    19.0 2062.56    47.4 2048.49    56.9 2043.59
    75.8 2032.88    85.3 2029.12    94.8 2027.82    97.8 2027.89   104.3 2028.05
   112.8 2028.48   123.3 2029.37   142.2 2031.63   151.6 2032.94   170.5 2035.83
   189.3 2039.26   208.1 2043.13   227.0 2047.35   245.8 2051.84   292.8 2063.53
   322.5 2065.20   332.4 2065.47   362.0 2065.01   381.8 2064.31   401.5 2064.37
   411.4 2064.12   431.2 2063.13   450.9 2061.81   470.7 2060.18   490.5 2058.95
#Mann= 3 , 0 , 0
       0     0.1       0    97.8   0.045       0   112.8     0.1       0
Bank Sta=    97.8,   112.8
Exp/Cntr=0.3,0.1

Type RM Length L Ch R = 1 ,18733.5,507.7,505.4,503
XS GIS Cut Line= 3
     1981626.992      401669.791     1982010.555      401369.364
     1982133.371      401282.448
#Sta/Elev= 30
       0 2074.18    89.5 2076.73    99.4 2076.87   109.4 2076.72   119.3 2076.09
   129.3 2075.20   139.2 2073.96   149.2 2071.93   159.1 2069.20   238.6 2045.27
   258.5 2039.52   278.4 2034.11   298.3 2029.27   318.2 2024.82   329.1 2023.28
   338.1 2023.10   344.1 2023.89   348.0 2024.41   358.0 2027.24   367.9 2030.68
   387.8 2036.46   457.4 2053.26   487.2 2059.82   524.8 2067.12   553.0 2072.08
   571.8 2075.18   590.6 2078.15   609.5 2080.82   628.3 2083.19   637.7 2083.82
#Mann= 3 , 0 , 0
       0     0.1       0   329.1   0.045       0   344.1     0.1       0
Bank Sta=   329.1,   344.1
Exp/Cntr=0.3,0.1

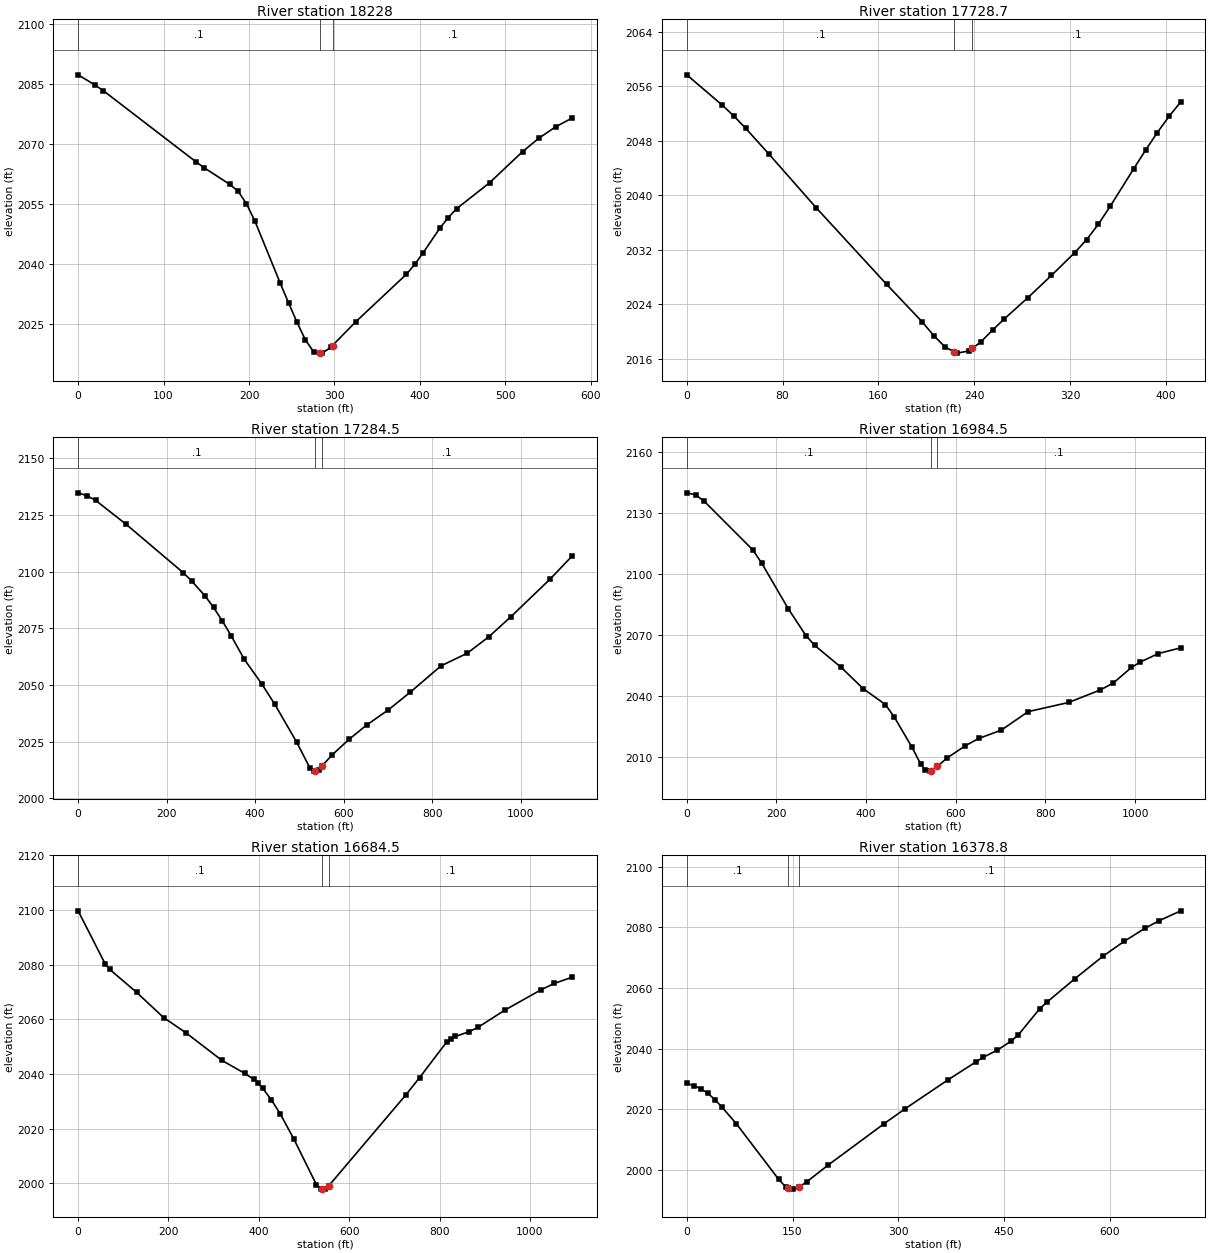
Type RM Length L Ch R = 1 ,18228,512.9,499.2,485.6
XS GIS Cut Line= 3
     1981899.076      402094.922     1982201.392      401798.275
     1982241.071      401649.006
#Sta/Elev= 30
       0 2087.34    19.7 2084.80    29.6 2083.35   137.9 2065.55   147.8 2064.02
   177.3 2059.92   187.2 2058.20   197.0 2055.04   206.8 2050.75   236.4 2035.22
   246.2 2030.23   256.1 2025.40   266.0 2020.93   275.8 2017.90   282.7 2017.71
   285.6 2017.63   295.5 2019.05   297.7 2019.54   325.0 2025.50   384.2 2037.39
   394.0 2039.87   403.8 2042.78   423.6 2049.02   433.2 2051.60   442.9 2053.81
   481.5 2060.30   520.1 2068.11   539.4 2071.50   558.7 2074.31   578.0 2076.50
#Mann= 3 , 0 , 0
       0     0.1       0   282.7   0.045       0   297.7     0.1       0
Bank Sta=   282.7,   297.7
Exp/Cntr=0.3,0.1

Type RM Length L Ch R = 1 ,17728.7,423.8,444.1,466.4
XS GIS Cut Line= 2
     1982522.602      402247.970     1982603.850      401843.622
#Sta/Elev= 28
       0 2057.71    29.5 2053.27    39.3 2051.66    49.1 2049.86    68.7 2046.04
   108.0 2038.18   166.9 2026.91   196.4 2021.43   206.2 2019.39   216.0 2017.65
   223.5 2017.01   225.8 2016.81   235.7 2017.14   238.5 2017.51   245.5 2018.45
   255.3 2020.20   265.1 2021.84   284.8 2024.96   304.4 2028.22   324.0 2031.59
   333.9 2033.50   343.7 2035.77   353.5 2038.38   373.2 2043.92   383.0 2046.62
   392.8 2049.21   402.6 2051.59   412.4 2053.73
#Mann= 3 , 0 , 0
       0     0.1       0   223.5   0.045       0   238.5     0.1       0
Bank Sta=   223.5,   238.5
Exp/Cntr=0.3,0.1

Type RM Length L Ch R = 1 ,17284.5,299.1,299.9,298.6
XS GIS Cut Line= 3
     1982283.082      402636.680     1982764.397      402384.665
     1983295.396      402169.411
#Sta/Elev= 30
       0 2134.71    19.8 2133.48    39.5 2131.40   108.7 2120.81   237.1 2099.59
   256.8 2095.82   286.5 2089.37   306.2 2084.18   326.0 2078.22   345.7 2071.80
   375.4 2061.38   414.9 2050.54   444.5 2041.51   493.9 2024.84   523.5 2013.60
   533.4 2012.06   535.8 2012.22   543.3 2012.71   550.8 2014.22   572.9 2018.98
   612.4 2026.09   652.0 2032.35   701.4 2039.10   750.8 2046.86   819.9 2058.42
   879.2 2063.99   928.6 2071.33   978.0 2080.09  1066.9 2096.73  1116.3 2106.82
#Mann= 3 , 0 , 0
       0     0.1       0   535.8   0.045       0   550.8     0.1       0
Bank Sta=   535.8,   550.8
Exp/Cntr=0.3,0.1

Type RM Length L Ch R = 1 ,16984.5,305,300,294.5
XS GIS Cut Line= 3
     1982425.055      402866.992     1982923.114      402630.606
     1983420.607      402394.828
#Sta/Elev= 30
       0 2139.79    19.7 2138.79    39.4 2135.54   147.7 2111.69   167.4 2105.18
   226.4 2082.90   265.8 2069.74   285.5 2064.90   344.6 2054.11   393.8 2043.66
   443.0 2035.93   462.7 2029.85   502.1 2015.07   521.8 2006.70   531.6 2003.88
   541.5 2003.26   543.8 2003.49   558.8 2005.62   581.3 2009.79   621.4 2015.74
   651.4 2019.29   701.4 2023.35   761.5 2032.45   851.6 2036.93   921.7 2043.02
   951.7 2046.51   991.7 2054.10  1011.8 2056.81  1051.8 2060.93  1101.8 2063.75
#Mann= 3 , 0 , 0
       0     0.1       0   543.8   0.045       0   558.8     0.1       0
Bank Sta=   543.8,   558.8
Exp/Cntr=0.3,0.1

Type RM Length L Ch R = 1 ,16684.5,314.3,305.7,297.6
XS GIS Cut Line= 3
     1982669.681      403204.864     1983099.679      402866.001
     1983521.496      402519.824
#Sta/Elev= 30
       0 2099.70    59.7 2080.36    69.7 2078.30   129.4 2069.89   189.1 2060.67
   238.9 2055.04   318.5 2044.95   368.3 2040.28   388.2 2038.12   398.2 2036.66
   408.1 2034.87   428.0 2030.48   447.9 2025.28   477.8 2016.11   527.6 1999.46
   537.5 1997.88     540 1997.91   547.5 1998.01     555 1999.14   726.1 2032.50
   755.8 2038.68   815.4 2051.64   825.3 2052.95   835.2 2053.74   865.0 2055.46
   884.8 2057.06   944.3 2063.35  1023.7 2070.73  1053.5 2073.12  1093.2 2075.38
#Mann= 3 , 0 , 0
       0     0.1       0     540   0.045       0     555     0.1       0
Bank Sta=     540,     555
Exp/Cntr=0.3,0.1

Type RM Length L Ch R = 1 ,16378.8,303.7,294.2,286.4
XS GIS Cut Line= 2
     1983246.271      403196.486     1983596.837      402589.943
#Sta/Elev= 30
       0 2028.51    10.0 2027.79    20.0 2026.79    30.0 2025.23    40.0 2023.14
    50.0 2020.67    70.1 2015.27   130.1 1996.93   140.1 1994.39     144 1994.09
   150.1 1993.63     159 1994.27   170.1 1996.04   200.2 2001.52   280.2 2015.28
   310.2 2020.24   370.3 2029.67   410.3 2035.65   420.3 2037.12   440.4 2039.50
   460.4 2042.53   470.4 2044.58   500.4 2053.12   510.4 2055.26   550.4 2063.07
   590.5 2070.54   620.5 2075.44   650.5 2079.81   670.5 2082.28   700.6 2085.49
#Mann= 3 , 0 , 0
       0     0.1       0     144   0.045       0     159     0.1       0
Bank Sta=     144,     159
Exp/Cntr=0.3,0.1

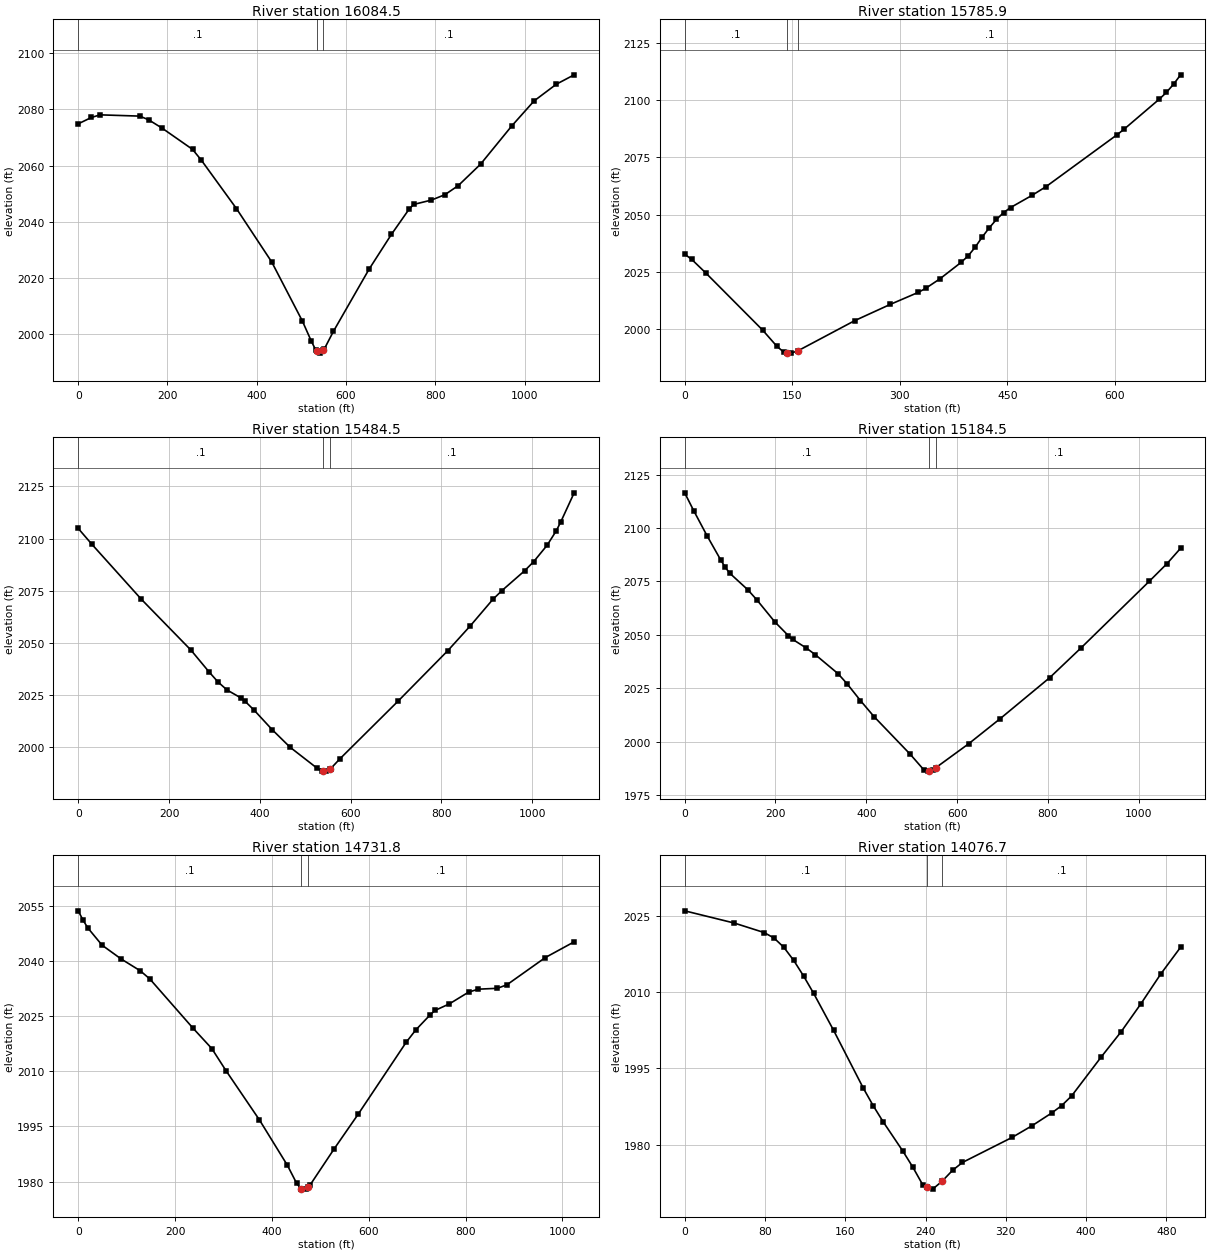
Type RM Length L Ch R = 1 ,16084.5,302.9,298.6,292.7
XS GIS Cut Line= 3
     1983530.383      403728.107     1983587.646      403189.406
     1983688.375      402628.875
#Sta/Elev= 30
       0 2074.84    29.6 2077.11    49.2 2078.04   137.9 2077.59   157.6 2076.29
   187.2 2073.39   256.1 2065.75   275.8 2061.92   354.6 2044.65   433.4 2025.70
   502.3 2004.61   522.0 1997.57   531.9 1994.39   534.2 1994.11   541.7 1993.20
   549.2 1994.38   551.7 1994.77   571.7 2000.92   651.6 2023.06   701.6 2035.44
   741.6 2044.51   751.6 2046.14   791.5 2047.70   821.5 2049.60   851.5 2052.84
   901.4 2060.46   971.4 2074.09  1021.3 2082.98  1071.3 2088.95  1111.2 2092.29
#Mann= 3 , 0 , 0
       0     0.1       0   534.2   0.045       0   549.2     0.1       0
Bank Sta=   534.2,   549.2
Exp/Cntr=0.3,0.1

Type RM Length L Ch R = 1 ,15785.9,288,301.3,315.8
XS GIS Cut Line= 2
     1983896.250      403311.744     1983838.078      402622.820
#Sta/Elev= 30
       0 2032.74     9.9 2030.41    29.6 2024.46   108.6 1999.56   128.4 1992.51
   138.3 1989.84   142.9 1989.67   148.2 1989.47   157.9 1990.49   237.0 2003.66
   286.4 2010.74   325.9 2016.06   335.8 2017.75   355.6 2021.89   385.2 2029.09
   395.1 2031.94   405.0 2035.78   414.8 2040.21   424.7 2044.27   434.6 2047.89
   444.5 2050.87   454.3 2053.10   484.0 2058.39   503.7 2062.23   602.5 2084.86
   612.4 2087.30   661.8 2100.52   671.6 2103.43   681.5 2107.00   691.4 2111.12
#Mann= 3 , 0 , 0
       0     0.1       0   142.9   0.045       0   157.9     0.1       0
Bank Sta=   142.9,   157.9
Exp/Cntr=0.3,0.1

Type RM Length L Ch R = 1 ,15484.5,299.3,300,298.8
XS GIS Cut Line= 3
     1983880.133      403761.292     1984142.858      403282.427
     1984428.085      402816.719
#Sta/Elev= 30
       0 2104.84    29.8 2097.30   139.0 2070.85   248.3 2046.44   288.0 2036.02
   307.9 2031.15   327.7 2027.32   357.5 2023.60   367.4 2021.90   387.3 2017.65
   427.0 2008.30   466.8 1999.80   526.3 1989.73   536.3 1988.44   538.7 1988.42
   546.2 1988.36   553.7 1989.28   556.1 1989.57   576.0 1994.18   705.1 2022.08
   814.3 2046.24   863.9 2058.16   913.6 2070.87   933.4 2075.03   983.1 2084.49
  1003.0 2088.85  1032.7 2096.74  1052.6 2103.59  1062.5 2107.82  1092.3 2121.92
#Mann= 3 , 0 , 0
       0     0.1       0   538.7   0.045       0   553.7     0.1       0
Bank Sta=   538.7,   553.7
Exp/Cntr=0.3,0.1

Type RM Length L Ch R = 1 ,15184.5,456.1,452.7,450.1
XS GIS Cut Line= 3
     1984128.077      403900.073     1984404.428      403429.253
     1984664.789      402948.889
#Sta/Elev= 30
       0 2116.46    19.8 2108.15    49.6 2096.25    79.4 2085.06    89.3 2081.63
    99.3 2078.86   139.0 2071.13   158.8 2066.44   198.5 2056.11   228.3 2049.68
   238.2 2047.88   268.0 2043.86   287.9 2040.73   337.5 2031.93   357.3 2027.26
   387.1 2019.30   416.9 2011.83   496.3 1994.29   526.1 1987.06   536.0 1986.30
   538.4 1986.45   545.9 1986.92   553.4 1987.94   625.4 1999.08   695.0 2010.85
   804.2 2030.05   873.8 2044.10  1022.8 2074.99  1062.5 2083.39  1092.3 2090.55
#Mann= 3 , 0 , 0
       0     0.1       0   538.4   0.045       0   553.4     0.1       0
Bank Sta=   538.4,   553.4
Exp/Cntr=0.3,0.1

Type RM Length L Ch R = 1 ,14731.8,665.1,655.1,645
XS GIS Cut Line= 4
     1984517.677      403983.662     1984786.629      403682.260
     1984815.149      403612.824     1985026.748      403110.276
#Sta/Elev= 30
       0 2053.66     9.8 2051.17    19.7 2049.03    49.3 2044.31    88.7 2040.56
   128.1 2037.35   147.8 2035.14   236.5 2021.82   275.9 2016.19   305.4 2010.14
   374.4 1996.75   432.1 1984.41   450.9 1979.58     460 1978.07   469.6 1977.94
     475 1978.59   479.0 1979.08   528.6 1988.89   578.2 1998.32   677.3 2017.88
   697.1 2021.24   726.9 2025.36   736.8 2026.55   766.5 2028.34   806.2 2031.53
   826.0 2032.34   865.7 2032.58   885.5 2033.54   964.8 2040.95  1024.3 2045.22
#Mann= 3 , 0 , 0
       0     0.1       0     460   0.045       0     475     0.1       0
Bank Sta=     460,     475
Exp/Cntr=0.3,0.1

Type RM Length L Ch R = 1 ,14076.7,381.2,392.1,404.3
XS GIS Cut Line= 2
     1985322.804      404237.586     1985290.682      403744.434
#Sta/Elev= 30
       0 2026.09    49.4 2023.68    79.1 2021.81    89.0 2020.73    98.8 2018.90
   108.7 2016.30   118.6 2013.20   128.5 2009.82   148.3 2002.56   177.9 1991.16
   187.8 1987.68   197.7 1984.51   217.4 1978.71   227.3 1975.56   237.2 1972.07
   241.5 1971.70   247.1 1971.21   256.5 1972.76   266.9 1974.91   276.8 1976.47
   326.2 1981.40   345.9 1983.68   365.7 1986.22   375.6 1987.67   385.5 1989.57
   415.1 1997.28   434.9 2002.24   454.7 2007.78   474.4 2013.63   494.2 2018.92
#Mann= 3 , 0 , 0
       0     0.1       0   241.5   0.045       0   256.5     0.1       0
Bank Sta=   241.5,   256.5
Exp/Cntr=0.3,0.1

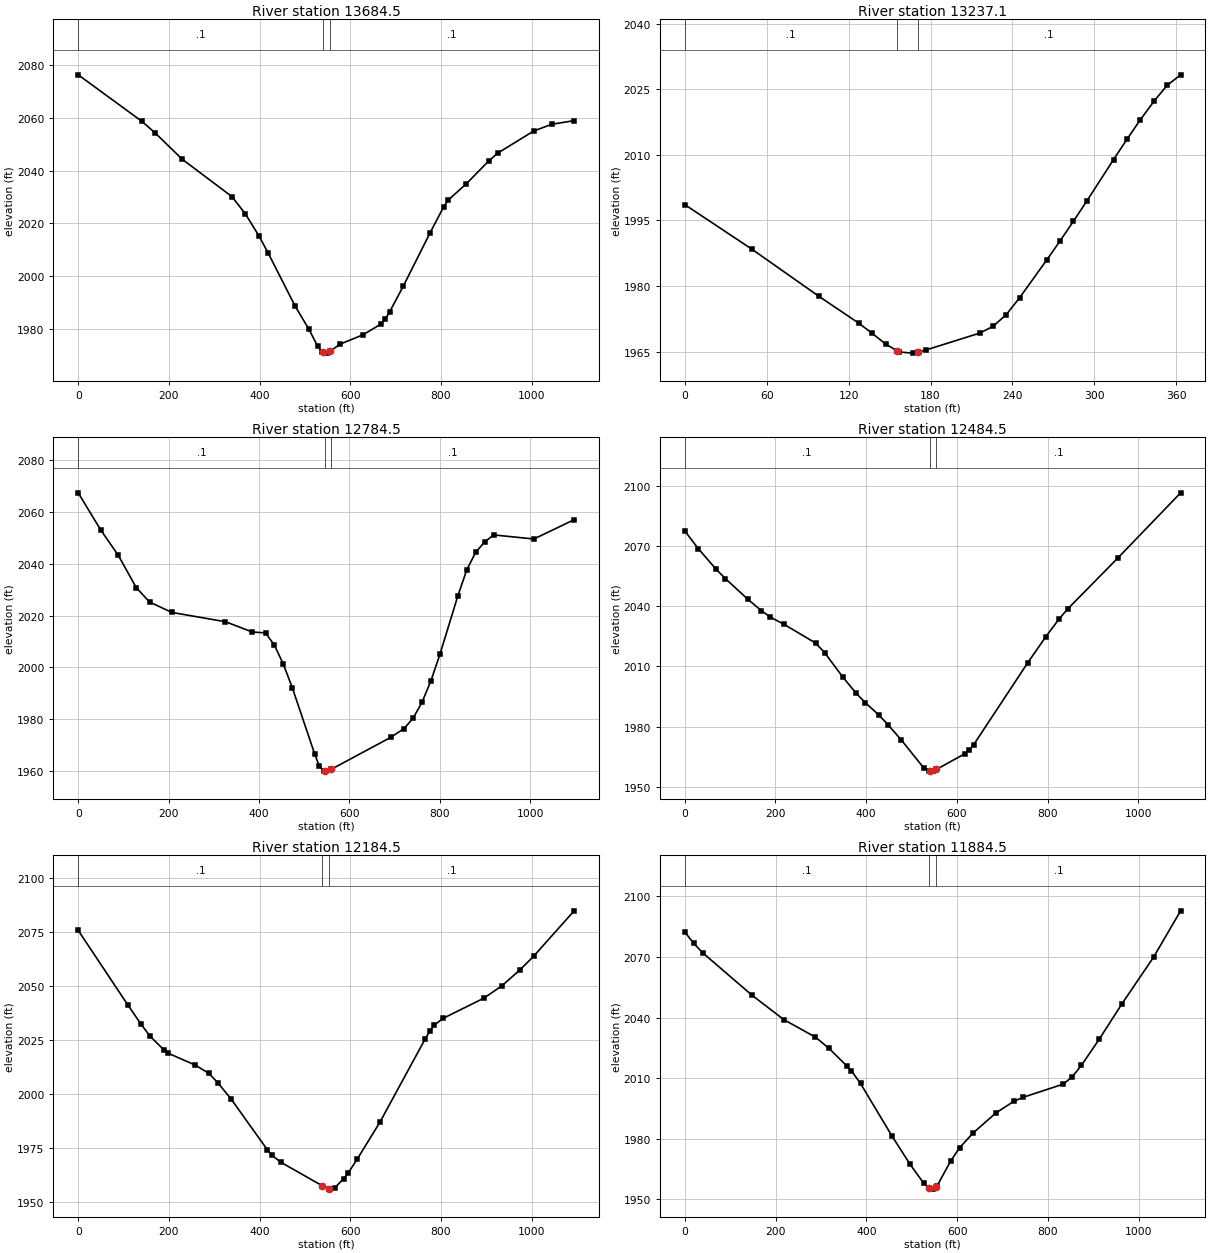
Type RM Length L Ch R = 1 ,13684.5,455.8,447.4,437.5
XS GIS Cut Line= 3
     1985455.452      404554.060     1985676.670      404052.454
     1985926.535      403567.423
#Sta/Elev= 30
       0 2076.33   139.6 2058.81   169.4 2054.36   229.3 2044.36   338.9 2030.21
   368.8 2023.62   398.7 2015.26   418.6 2008.93   478.4 1988.68   508.4 1980.04
   528.3 1973.44   538.2 1971.21   540.7 1971.13   548.2 1970.88   555.7 1971.63
   578.0 1974.30   627.6 1977.79   667.3 1981.84   677.2 1983.76   687.1 1986.60
   716.9 1996.23   776.4 2016.58   806.1 2026.34   816.1 2028.88   855.8 2035.02
   905.4 2043.70   925.2 2046.67  1004.6 2055.04  1044.2 2057.59  1093.8 2058.97
#Mann= 3 , 0 , 0
       0     0.1       0   540.7   0.045       0   555.7     0.1       0
Bank Sta=   540.7,   555.7
Exp/Cntr=0.3,0.1

Type RM Length L Ch R = 1 ,13237.1,447.4,452.5,458.2
XS GIS Cut Line= 2
     1986048.362      404437.871     1986063.478      404075.092
#Sta/Elev= 25
       0 1998.63    49.1 1988.44    98.1 1977.67   127.6 1971.46   137.4 1969.14
   147.2 1966.70   155.7 1965.15   157.0 1964.91   166.8 1964.64   170.7 1964.92
   176.6 1965.35   215.9 1969.21   225.7 1970.75   235.5 1973.46   245.3 1977.35
   265.0 1985.91   274.8 1990.29   284.6 1994.79   294.4 1999.42   314.0 2008.92
   323.8 2013.55   333.6 2018.01   343.5 2022.22   353.3 2025.92   363.1 2028.30
#Mann= 3 , 0 , 0
       0     0.1       0   155.7   0.045       0   170.7     0.1       0
Bank Sta=   155.7,   170.7
Exp/Cntr=0.3,0.1

Type RM Length L Ch R = 1 ,12784.5,296.1,300,302.9
XS GIS Cut Line= 3
     1986329.001      404947.540     1986475.212      404414.517
     1986633.337      403893.247
#Sta/Elev= 30
       0 2067.49    49.4 2053.24    88.8 2043.28   128.3 2030.84   157.9 2025.24
   207.3 2021.22   325.7 2017.63   384.9 2013.67   414.5 2013.29   434.3 2008.50
   454.0 2001.18   473.8 1992.06   523.1 1966.54   533.0 1961.99   542.8 1959.83
   545.2 1959.84   560.2 1960.56   691.4 1972.88   721.1 1976.32   740.9 1980.25
   760.7 1986.44   780.5 1994.80   800.3 2004.95   839.9 2027.55   859.7 2037.67
   879.6 2044.52   899.4 2048.49   919.2 2051.21  1008.3 2049.63  1097.4 2057.10
#Mann= 3 , 0 , 0
       0     0.1       0   545.2   0.045       0   560.2     0.1       0
Bank Sta=   545.2,   560.2
Exp/Cntr=0.3,0.1

Type RM Length L Ch R = 1 ,12484.5,304.5,300,297.6
XS GIS Cut Line= 3
     1986519.388      405022.248     1986752.906      404527.145
     1986976.431      404029.390
#Sta/Elev= 30
       0 2077.80    29.9 2068.90    69.7 2058.46    89.6 2053.94   139.3 2043.54
   169.2 2037.87   189.1 2034.61   219.0 2031.05   288.6 2021.68   308.5 2016.88
   348.4 2004.74   378.2 1996.54   398.1 1991.92   428.0 1985.71   447.9 1980.97
   477.7 1973.18   527.5 1959.13   537.5 1957.70   539.9 1957.71   547.4 1957.76
   554.9 1958.55   616.8 1966.32   626.8 1968.03   636.7 1970.83   755.7 2011.73
   795.4 2024.71   825.2 2033.78   845.0 2038.95   954.2 2064.09  1093.0 2096.77
#Mann= 3 , 0 , 0
       0     0.1       0   539.9   0.045       0   554.9     0.1       0
Bank Sta=   539.9,   554.9
Exp/Cntr=0.3,0.1

Type RM Length L Ch R = 1 ,12184.5,299.2,299.9,298.7
XS GIS Cut Line= 3
     1986892.346      405184.040     1987022.647      404654.153
     1987192.829      404133.399
#Sta/Elev= 30
       0 2075.75   109.1 2041.29   138.9 2032.19   158.7 2026.66   188.5 2020.48
   198.4 2018.83   258.0 2013.36   287.7 2009.55   307.6 2005.22   337.3 1997.58
   416.7 1974.20   426.6 1971.66   446.5 1968.37   538.2 1957.41   553.2 1956.03
   555.6 1955.88   565.6 1956.52   585.5 1960.69   595.5 1963.40   615.4 1969.86
   665.2 1986.88   764.8 2025.36   774.8 2028.96   784.7 2031.80   804.7 2035.01
   894.3 2044.34   934.2 2050.07   974.0 2057.46  1003.9 2063.72  1093.5 2084.81
#Mann= 3 , 0 , 0
       0     0.1       0   538.2   0.045       0   553.2     0.1       0
Bank Sta=   538.2,   553.2
Exp/Cntr=0.3,0.1

Type RM Length L Ch R = 1 ,11884.5,308.8,300,291.4
XS GIS Cut Line= 3
     1987162.205      405262.619     1987310.419      404737.134
     1987451.012      404209.473
#Sta/Elev= 30
       0 2082.42    19.8 2076.78    39.7 2072.06   148.9 2050.94   218.4 2038.98
   287.9 2030.31   317.7 2024.80   357.4 2015.98   367.3 2013.61   387.2 2007.38
   456.6 1981.33   496.4 1967.35   526.1 1958.08   538.5 1955.63   546.0 1955.09
   553.5 1956.32   555.9 1956.72   585.7 1968.97   605.6 1975.65   635.3 1982.89
   685.0 1992.74   724.7 1998.54   744.6 2000.49   833.9 2007.08   853.8 2010.76
   873.6 2016.34   913.3 2029.45   963.0 2046.84  1032.5 2069.89  1092.1 2092.84
#Mann= 3 , 0 , 0
       0     0.1       0   538.5   0.045       0   553.5     0.1       0
Bank Sta=   538.5,   553.5
Exp/Cntr=0.3,0.1