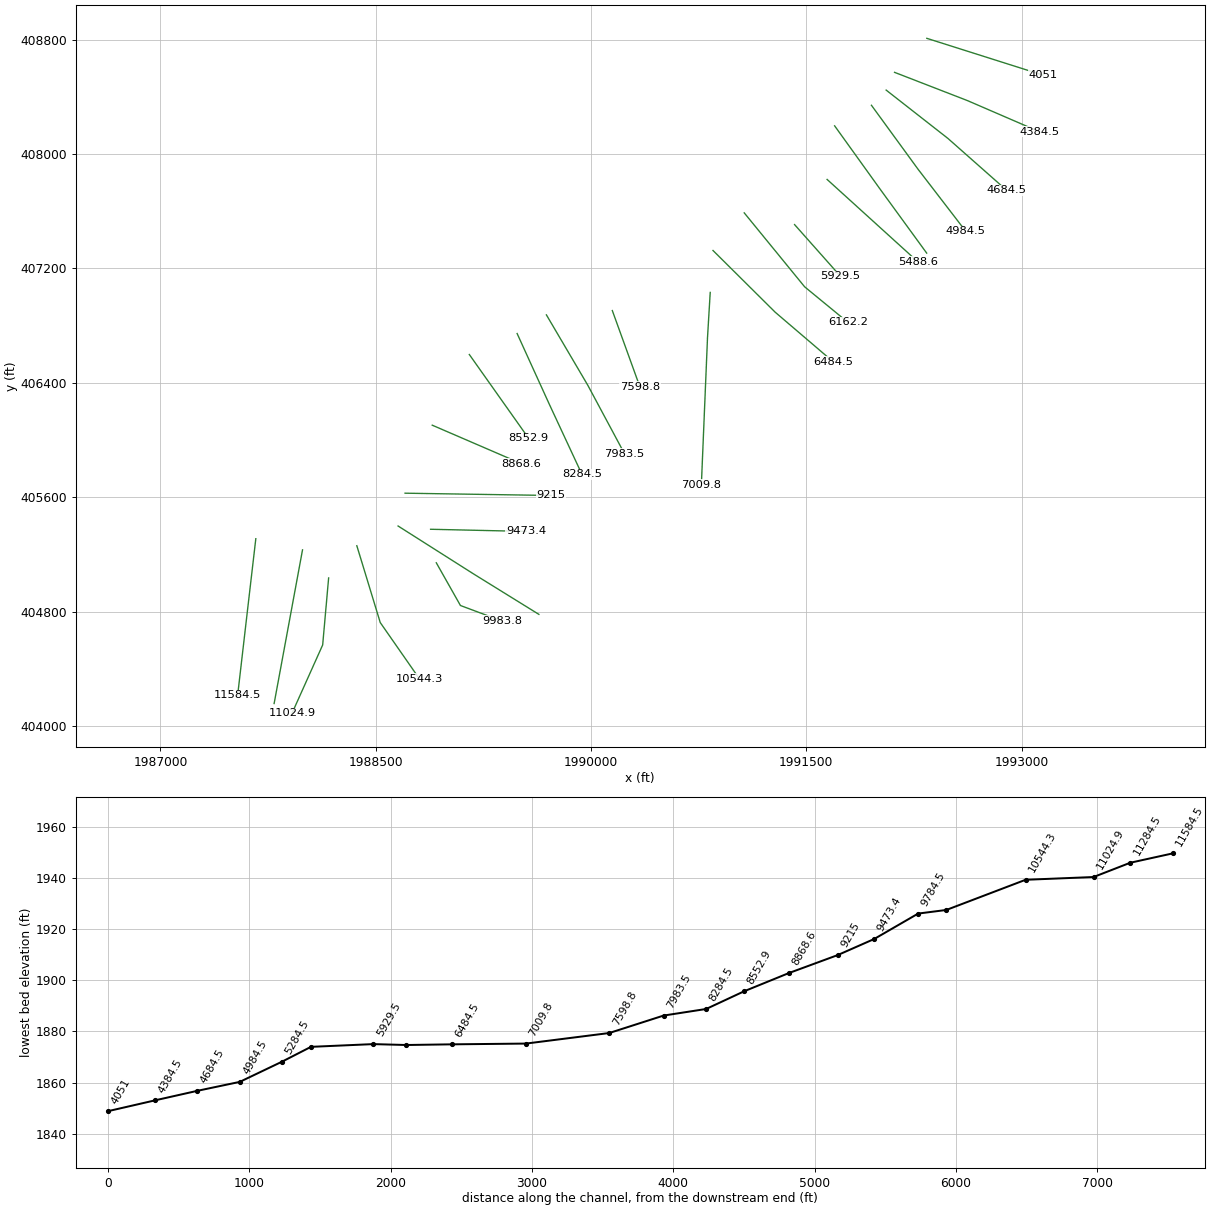
HEC-RAS study LaurelCrk4.prj: LaurelCrk4

--- LaurelCrk4.g01 (geometry) --- (continued)

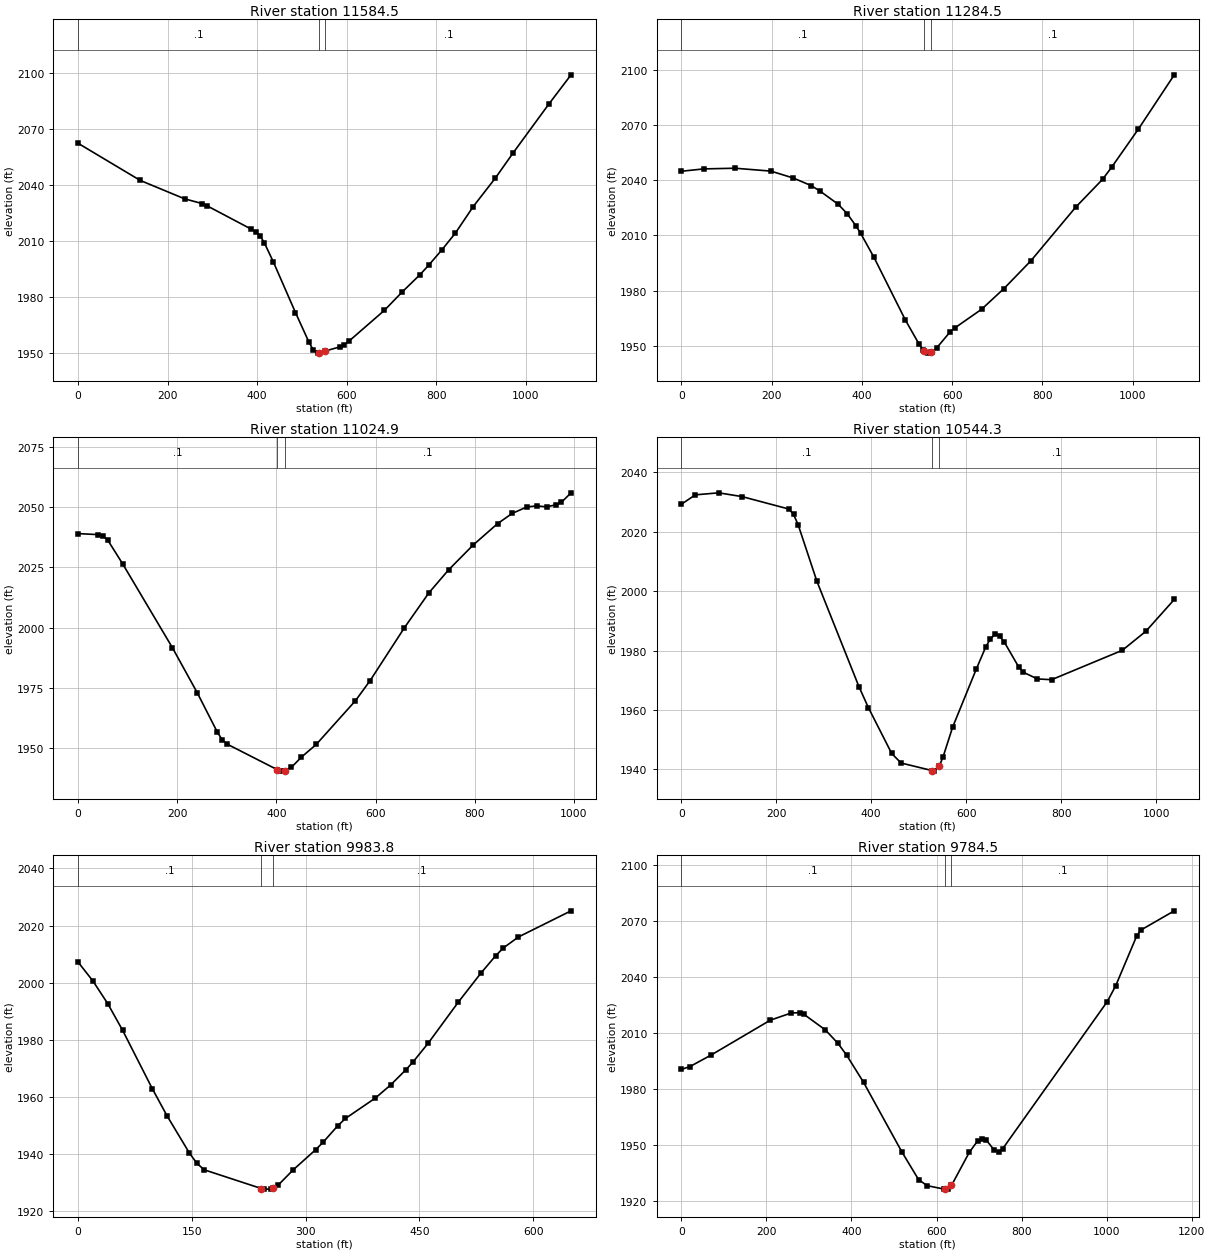
Type RM Length L Ch R = 1 ,11584.5,301.5,300,298.5
XS GIS Cut Line= 3
     1987664.834      405310.891     1987602.087      404769.679
     1987538.322      404217.626
#Sta/Elev= 30
       0 2062.45   138.7 2042.51   237.8 2032.62   277.4 2030.03   287.3 2028.95
   386.3 2016.37   396.2 2014.98   406.2 2012.88   416.1 2008.85   435.9 1998.77
   485.4 1971.51   515.1 1955.81   525.0 1951.42   534.9 1949.74   537.3 1949.83
   552.3 1950.91   584.5 1953.10   594.5 1954.29   604.4 1956.10   683.8 1972.70
   723.5 1982.56   763.2 1991.84   783.0 1997.02   812.8 2005.37   842.6 2014.29
   882.2 2028.45   931.9 2043.86   971.6 2057.39  1050.9 2083.47  1100.6 2099.21
#Mann= 3 , 0 , 0
       0     0.1       0   537.3   0.045       0   552.3     0.1       0
Bank Sta=   537.3,   552.3
Exp/Cntr=0.3,0.1

Type RM Length L Ch R = 1 ,11284.5,256.8,259.5,262.3
XS GIS Cut Line= 3
     1987990.239      405232.977     1987891.324      404696.012
     1987792.408      404159.046
#Sta/Elev= 30
       0 2044.82    49.6 2046.10   119.1 2046.47   198.6 2044.90   248.2 2041.14
   287.9 2037.01   307.8 2033.98   347.4 2026.92   367.3 2021.85   387.2 2015.07
   397.1 2011.21   426.9 1998.04   496.4 1964.04   526.2 1951.18   536.1 1947.55
   538.5 1947.19   546.0 1946.08   553.5 1946.53   555.9 1946.67   565.8 1948.94
   595.6 1957.64   605.6 1959.71   665.1 1969.88   714.8 1981.14   774.3 1996.19
   873.6 2025.31   933.2 2040.45   953.0 2046.92  1012.6 2067.76  1092.0 2097.18
#Mann= 3 , 0 , 0
       0     0.1       0   538.5   0.045       0   553.5     0.1       0
Bank Sta=   538.5,   553.5
Exp/Cntr=0.3,0.1

Type RM Length L Ch R = 1 ,11024.9,472.8,480.6,488.5
XS GIS Cut Line= 3
     1988172.131      405036.834     1988130.563      404568.244
     1987916.654      404090.169
#Sta/Elev= 30
       0 2039.03    40.0 2038.62    50.0 2038.15    60.0 2036.28    90.1 2026.43
   190.2 1991.72   240.2 1973.07   280.3 1956.89   290.3 1953.57   300.3 1951.73
   401.9 1941.08   410.4 1940.49   416.9 1940.61   430.4 1942.10   450.4 1946.29
   480.3 1951.56   559.4 1969.70   589.0 1978.05   658.2 2000.01   707.6 2014.48
   747.1 2023.96   796.5 2034.24   846.0 2043.17   875.6 2047.42   905.2 2050.10
   925.0 2050.53   944.8 2050.14   964.5 2051.01   974.4 2051.96   994.2 2055.95
#Mann= 3 , 0 , 0
       0     0.1       0   401.9   0.045       0   416.9     0.1       0
Bank Sta=   401.9,   416.9
Exp/Cntr=0.3,0.1

Type RM Length L Ch R = 1 ,10544.3,555.5,560.5,565.4
XS GIS Cut Line= 3
     1988368.564      405261.909     1988531.837      404724.718
     1988803.845      404333.005
#Sta/Elev= 30
       0 2029.27    29.6 2032.45    78.8 2033.13   128.0 2031.86   226.6 2027.67
   236.4 2025.89   246.2 2022.35   285.6 2003.36   374.3 1967.82   394.0 1960.82
   443.2 1945.35   463.0 1942.14   528.2 1939.60   531.9 1939.41   543.2 1941.01
   551.6 1944.30   571.4 1954.15   621.1 1973.67   640.9 1981.09   650.9 1983.93
   660.8 1985.48   670.7 1984.80   680.7 1982.78   710.5 1974.54   720.4 1972.71
   750.2 1970.45   780.0 1970.20   929.1 1980.11   978.7 1986.53  1038.4 1997.21
#Mann= 3 , 0 , 0
       0     0.1       0   528.2   0.045       0   543.2     0.1       0
Bank Sta=   528.2,   543.2
Exp/Cntr=0.3,0.1

Type RM Length L Ch R = 1 ,9983.8,188.3,199.3,210.7
XS GIS Cut Line= 3
     1988922.252      405142.645     1989090.416      404844.108
     1989378.245      404736.093
#Sta/Elev= 30
       0 2007.18    19.6 2000.56    39.2 1992.58    58.7 1983.29    97.9 1962.80
   117.5 1953.21   146.8 1940.25   156.6 1936.67   166.4 1934.36   241.6 1927.81
   244.7 1927.59   254.5 1927.60   256.6 1927.92   264.3 1929.11   283.9 1934.40
   313.3 1941.41   323.1 1944.02   342.6 1949.84   352.6 1952.36   392.2 1959.55
   412.1 1964.09   431.9 1969.32   441.8 1972.20   461.6 1978.71   501.3 1993.10
   531.1 2003.27   550.9 2009.48   560.8 2012.13   580.6 2015.97   650.1 2025.15
#Mann= 3 , 0 , 0
       0     0.1       0   241.6   0.045       0   256.6     0.1       0
Bank Sta=   241.6,   256.6
Exp/Cntr=0.3,0.1

Type RM Length L Ch R = 1 ,9784.5,298.7,311,323.1
XS GIS Cut Line= 3
     1988656.053      405399.690     1989185.488      405062.519
     1989636.864      404782.161
#Sta/Elev= 30
       0 1990.47    19.9 1991.95    69.7 1998.14   209.2 2016.91   259.0 2020.83
   279.0 2020.92   288.9 2019.97   338.8 2011.67   368.6 2004.40   388.6 1998.17
   428.4 1983.58   518.1 1946.37   557.9 1931.28   577.9 1928.06   617.7 1926.18
   620.2 1926.24   627.7 1926.40   635.2 1928.13   676.9 1945.87   696.6 1952.07
   706.4 1953.25   716.2 1952.77   735.9 1947.09   745.8 1945.90   755.6 1947.88
  1001.6 2026.94  1021.3 2035.42  1070.5 2062.04  1080.3 2065.30  1159.0 2075.65
#Mann= 3 , 0 , 0
       0     0.1       0   620.2   0.045       0   635.2     0.1       0
Bank Sta=   620.2,   635.2
Exp/Cntr=0.3,0.1

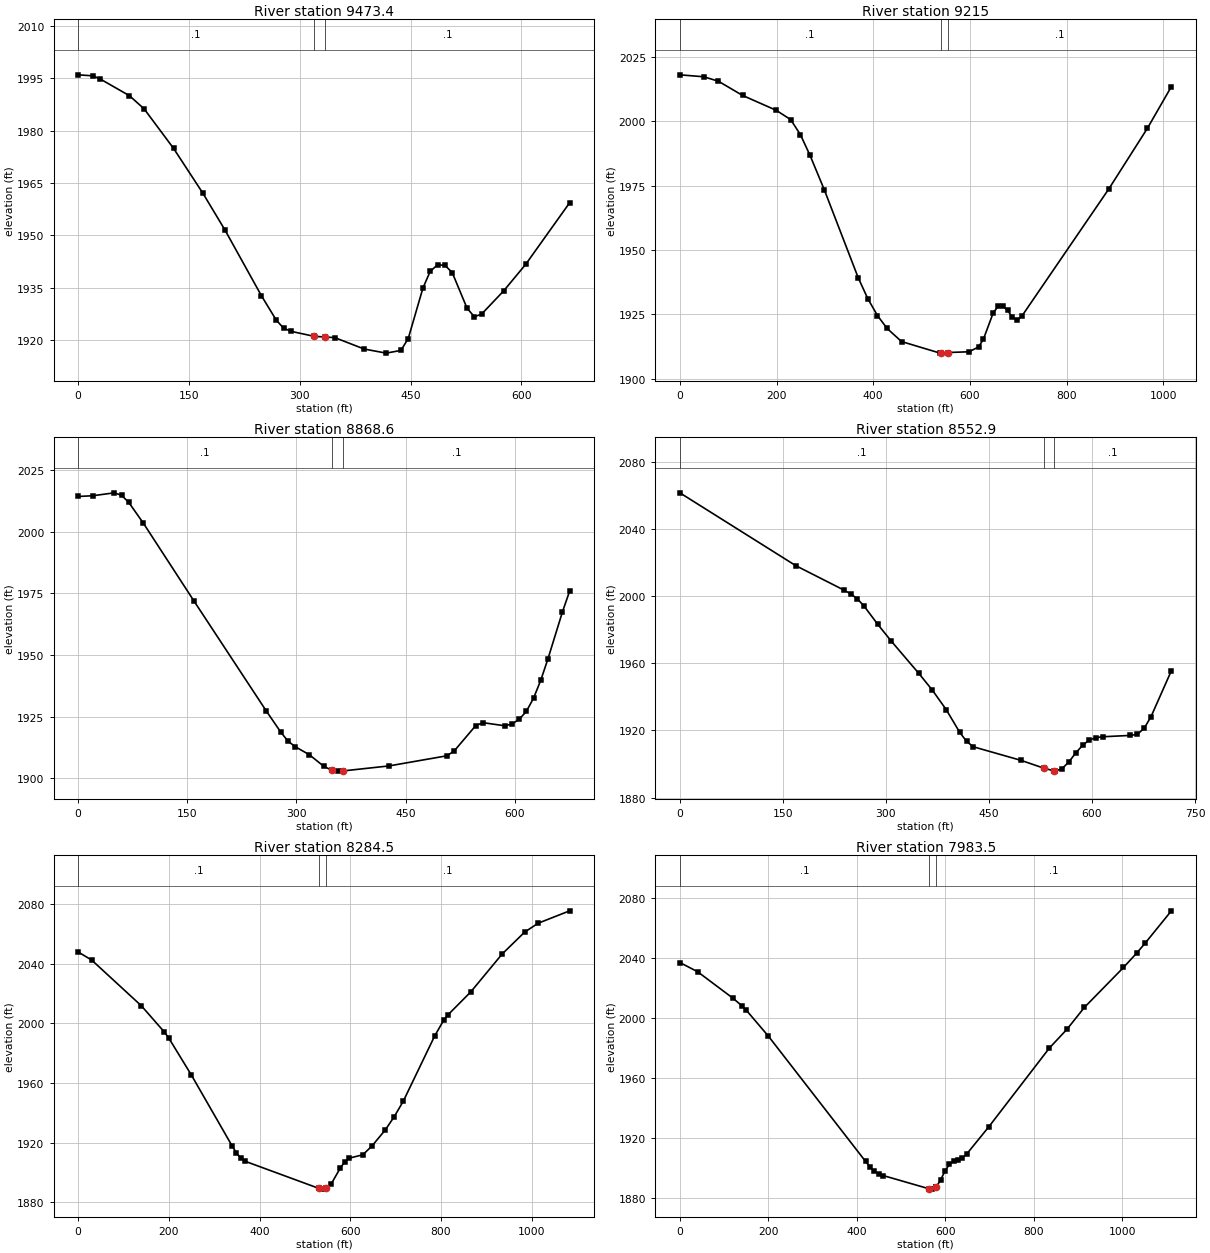
Type RM Length L Ch R = 1 ,9473.4,258.3,258.5,258.6
XS GIS Cut Line= 2
     1988882.573      405376.940     1989547.668      405361.824
#Sta/Elev= 30
       0 1995.99    19.9 1995.70    29.8 1994.81    69.5 1990.00    89.4 1986.22
   129.1 1974.93   168.8 1962.08   198.6 1951.57   248.2 1932.64   268.1 1925.71
   278.0 1923.40   288.0 1922.48   319.6 1921.03   334.6 1920.84   347.5 1920.66
   387.2 1917.39   417.0 1916.22   436.9 1917.00   446.8 1920.39   466.7 1934.87
   476.6 1939.68   486.5 1941.52   496.5 1941.40   506.4 1939.29   526.3 1929.15
   536.2 1926.65   546.1 1927.40   575.9 1934.04   605.7 1941.64   665.3 1959.33
#Mann= 3 , 0 , 0
       0     0.1       0   319.6   0.045       0   334.6     0.1       0
Bank Sta=   319.6,   334.6
Exp/Cntr=0.3,0.1

Type RM Length L Ch R = 1 ,9215,355.3,346.2,337.1
XS GIS Cut Line= 2
     1988704.621      405629.063     1989721.500      405613.124
#Sta/Elev= 30
       0 2018.05    49.8 2017.29    79.8 2015.55   129.6 2010.06   199.4 2004.26
   229.3 2000.64   249.3 1994.84   269.2 1986.81   299.1 1973.26   368.9 1939.25
   388.8 1931.08   408.8 1924.52   428.7 1919.52   458.6 1914.41   538.4 1909.91
   539.5 1909.92   554.5 1910.15   598.2 1910.43   618.2 1912.33   628.2 1915.40
   648.1 1925.44   658.1 1928.06   668.0 1928.20   678.0 1926.56   688.0 1923.86
   697.9 1922.63   707.9 1924.38   887.4 1973.68   967.2 1997.23  1017.0 2013.48
#Mann= 3 , 0 , 0
       0     0.1       0   539.5   0.045       0   554.5     0.1       0
Bank Sta=   539.5,   554.5
Exp/Cntr=0.3,0.1

Type RM Length L Ch R = 1 ,8868.6,327.8,315.4,303
XS GIS Cut Line= 2
     1988893.910      406104.387     1989513.658      405836.082
#Sta/Elev= 30
       0 2014.39    19.9 2014.68    49.7 2015.87    59.6 2014.88    69.5 2012.01
    89.4 2003.65   158.9 1972.06   258.2 1927.42   278.1 1918.82   288.0 1915.14
   297.9 1912.83   317.8 1909.49   337.7 1904.75   348.9 1903.19   357.5 1902.85
   363.9 1902.93   427.0 1904.96   506.5 1909.07   516.4 1910.94   546.2 1921.32
   556.2 1922.53   586.0 1921.27   595.9 1921.97   605.8 1923.85   615.7 1927.07
   625.7 1932.47   635.6 1939.74   645.5 1948.47   665.4 1967.51   675.3 1975.99
#Mann= 3 , 0 , 0
       0     0.1       0   348.9   0.045       0   363.9     0.1       0
Bank Sta=   348.9,   363.9
Exp/Cntr=0.3,0.1

Type RM Length L Ch R = 1 ,8552.9,272.7,268.5,264.4
XS GIS Cut Line= 2
     1989152.256      406598.348     1989564.674      406013.692
#Sta/Elev= 30
       0 2061.71   168.9 2018.24   238.5 2003.77   248.4 2001.54   258.4 1998.47
   268.3 1994.08   288.2 1983.20   308.0 1973.14   347.8 1954.03   367.7 1943.94
   387.6 1932.48   407.4 1918.86   417.4 1913.44   427.3 1910.24   496.9 1902.12
   529.7 1897.52   544.7 1895.88   546.6 1895.74   556.5 1897.24   566.4 1901.32
   576.4 1906.64   586.3 1911.18   596.2 1914.35   606.2 1915.75   616.1 1916.25
   655.9 1917.04   665.8 1917.70   675.7 1921.19   685.7 1928.12   715.5 1955.66
#Mann= 3 , 0 , 0
       0     0.1       0   529.7   0.045       0   544.7     0.1       0
Bank Sta=   529.7,   544.7
Exp/Cntr=0.3,0.1

Type RM Length L Ch R = 1 ,8284.5,299,301,302.1
XS GIS Cut Line= 3
     1989485.316      406744.919     1989707.822      406254.536
     1989937.441      405759.966
#Sta/Elev= 30
       0 2047.79    29.9 2042.36   139.6 2011.66   189.5 1994.34   199.4 1990.32
   249.3 1965.52   339.1 1918.00   349.0 1913.09   359.0 1909.44   369.0 1907.40
     531 1889.29   538.5 1888.81     546 1889.33   558.3 1892.44   578.2 1903.01
   588.1 1907.16   598.0 1909.59   627.7 1911.83   647.6 1917.62   677.3 1928.50
   697.1 1937.43   717.0 1947.77   786.4 1991.62   806.2 2002.08   816.1 2005.82
   865.7 2020.99   935.1 2046.46   984.6 2061.10  1014.4 2067.06  1083.8 2075.36
#Mann= 3 , 0 , 0
       0     0.1       0     531   0.045       0     546     0.1       0
Bank Sta=     531,     546
Exp/Cntr=0.3,0.1

Type RM Length L Ch R = 1 ,7983.5,388.3,384.6,381.6
XS GIS Cut Line= 3
     1989689.379      406875.293     1989977.605      406383.666
     1990232.780      405906.266
#Sta/Elev= 30
       0 2037.23    40.0 2031.14   120.0 2013.46   140.0 2008.46   150.0 2005.52
   200.0 1988.23   419.9 1904.67   429.9 1900.94   439.9 1897.99   449.9 1896.24
   459.9 1895.26   563.7 1886.42   569.9 1886.23   578.7 1887.65   579.7 1887.81
   589.6 1892.43   599.4 1898.32   609.3 1902.74   619.1 1905.07   628.9 1905.78
   638.8 1907.00   648.6 1909.69   697.8 1927.54   835.6 1980.34   875.0 1992.72
   914.4 2007.30  1002.9 2033.96  1032.5 2043.46  1052.2 2050.28  1111.2 2071.70
#Mann= 3 , 0 , 0
       0     0.1       0   563.7   0.045       0   578.7     0.1       0
Bank Sta=   563.7,   578.7
Exp/Cntr=0.3,0.1

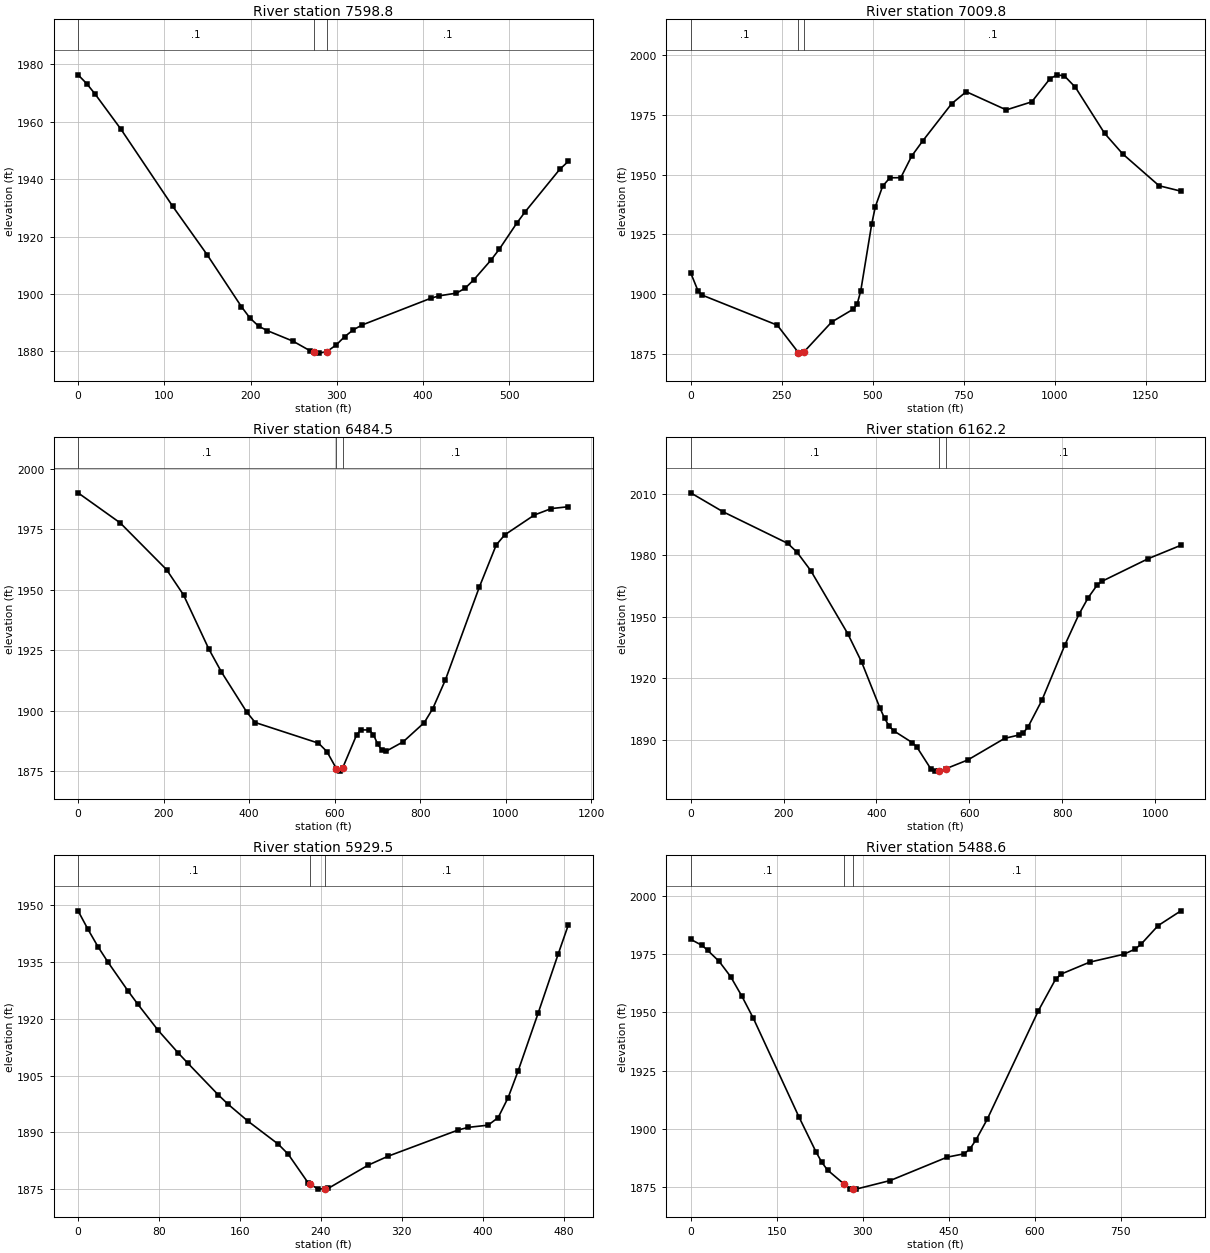
Type RM Length L Ch R = 1 ,7598.8,598.2,588.9,579.7
XS GIS Cut Line= 2
     1990148.521      406905.524     1990341.248      406370.803
#Sta/Elev= 30
       0 1976.35    10.0 1973.29    19.9 1969.60    49.9 1957.33   109.7 1930.56
   149.6 1913.71   189.5 1895.55   199.4 1891.59   209.4 1888.78   219.4 1887.23
   249.3 1883.55   269.2 1880.18   273.2 1879.86   279.2 1879.39   288.2 1879.86
   299.2 1882.21   309.1 1885.12   319.1 1887.49   329.1 1889.16   408.8 1898.48
   418.8 1899.35   438.8 1900.30   448.7 1901.98   458.7 1904.88   478.6 1911.74
   488.6 1915.67   508.6 1924.63   518.5 1928.66   558.4 1943.38   568.4 1946.19
#Mann= 3 , 0 , 0
       0     0.1       0   273.2   0.045       0   288.2     0.1       0
Bank Sta=   273.2,   288.2
Exp/Cntr=0.3,0.1

Type RM Length L Ch R = 1 ,7009.8,506,525.3,546.1
XS GIS Cut Line= 3
     1990830.621      407032.119     1990811.681      406715.321
     1990768.899      405686.708
#Sta/Elev= 30
       0 1908.84    19.8 1901.44    29.8 1899.65   238.0 1886.96     296 1875.47
   297.5 1875.26     311 1875.74   387.3 1888.28   447.3 1893.72   457.3 1895.73
   467.3 1901.38   497.3 1929.28   507.3 1936.54   527.3 1945.12   547.2 1948.66
   577.2 1948.70   607.2 1957.76   637.2 1964.03   717.2 1979.71   757.2 1984.69
   867.1 1977.08   937.1 1980.45   987.0 1990.11  1007.0 1991.76  1027.0 1991.28
  1057.0 1986.54  1137.0 1967.31  1186.9 1958.66  1286.9 1945.33  1346.9 1943.06
#Mann= 3 , 0 , 0
       0     0.1       0     296   0.045       0     311     0.1       0
Bank Sta=     296,     311
Exp/Cntr=0.3,0.1

Type RM Length L Ch R = 1 ,6484.5,324.7,322.1,317.8
XS GIS Cut Line= 3
     1990850.065      407325.346     1991283.266      406894.048
     1991689.072      406546.215
#Sta/Elev= 30
       0 1990.18    98.6 1977.72   207.0 1958.35   246.5 1947.93   305.6 1925.54
   335.2 1915.99   394.4 1899.39   414.1 1895.09   562.0 1886.54   581.7 1883.05
   603.8 1876.00   611.3 1874.96   618.8 1876.41   650.9 1889.87   660.8 1892.03
   680.6 1892.00   690.5 1890.03   700.4 1886.12   710.3 1883.62   720.2 1883.22
   759.8 1887.08   809.2 1895.04   829.0 1900.79   858.7 1912.76   937.9 1951.14
   977.5 1968.62   997.3 1972.77  1066.6 1981.00  1106.2 1983.66  1145.8 1984.42
#Mann= 3 , 0 , 0
       0     0.1       0   603.8   0.045       0   618.8     0.1       0
Bank Sta=   603.8,   618.8
Exp/Cntr=0.3,0.1

Type RM Length L Ch R = 1 ,6162.2,231.8,232.7,233.7
XS GIS Cut Line= 3
     1991067.546      407588.347     1991488.159      407071.798
     1991788.585      406824.277
#Sta/Elev= 30
       0 2010.47    69.6 2001.23   208.8 1985.82   228.7 1981.57   258.5 1972.51
   338.0 1941.81   367.9 1927.98   407.6 1905.39   417.6 1900.38   427.5 1896.60
   437.5 1894.31   477.2 1888.58   487.2 1886.35   517.0 1875.79   526.9 1874.70
   535.6 1874.91   550.6 1875.98   596.5 1880.14   676.1 1890.71   706.1 1892.28
   716.0 1893.42   726.0 1896.14   756.0 1909.21   805.9 1936.39   835.8 1951.18
   855.8 1959.32   875.7 1965.66   885.7 1967.34   985.5 1978.39  1055.4 1984.88
#Mann= 3 , 0 , 0
       0     0.1       0   535.6   0.045       0   550.6     0.1       0
Bank Sta=   535.6,   550.6
Exp/Cntr=0.3,0.1

Type RM Length L Ch R = 1 ,5929.5,438.3,440.6,443
XS GIS Cut Line= 2
     1991418.248      407506.377     1991739.459      407143.598
#Sta/Elev= 30
       0 1948.41     9.9 1943.49    19.8 1938.91    29.7 1934.83    49.4 1927.29
    59.3 1923.72    79.1 1916.93    98.9 1910.98   108.8 1908.17   138.4 1899.96
   148.3 1897.43   168.1 1892.94   197.8 1886.93   207.7 1884.28   227.4 1876.72
   229.5 1876.37   237.3 1875.05   244.5 1875.18   247.2 1875.23   286.8 1881.37
   306.6 1883.74   375.8 1890.64   385.7 1891.33   405.4 1891.91   415.3 1893.91
   425.2 1899.19   435.1 1906.25   454.9 1921.49   474.7 1937.05   484.6 1944.64
#Mann= 3 , 0 , 0
       0     0.1       0   229.5   0.045       0   244.5     0.1       0
Bank Sta=   229.5,   244.5
Exp/Cntr=0.3,0.1

Type RM Length L Ch R = 1 ,5488.6,208.8,204,199.4
XS GIS Cut Line= 2
     1991644.985      407821.919     1992277.216      407246.350
#Sta/Elev= 30
       0 1981.41    19.9 1978.80    29.8 1976.64    49.7 1971.91    69.6 1965.39
    89.5 1956.86   109.4 1947.39   188.9 1904.98   218.7 1889.93   228.7 1885.51
   238.6 1882.20   267.6 1876.13   278.4 1874.14   282.6 1874.07   288.3 1873.98
   348.0 1877.68   447.4 1887.74   477.2 1889.19   487.1 1891.32   497.1 1894.96
   517.0 1903.94   606.4 1950.71   636.3 1964.21   646.2 1966.49   695.9 1971.61
   755.6 1975.01   775.4 1977.26   785.4 1979.30   815.2 1987.31   855.0 1993.68
#Mann= 3 , 0 , 0
       0     0.1       0   267.6   0.045       0   282.6     0.1       0
Bank Sta=   267.6,   282.6
Exp/Cntr=0.3,0.1

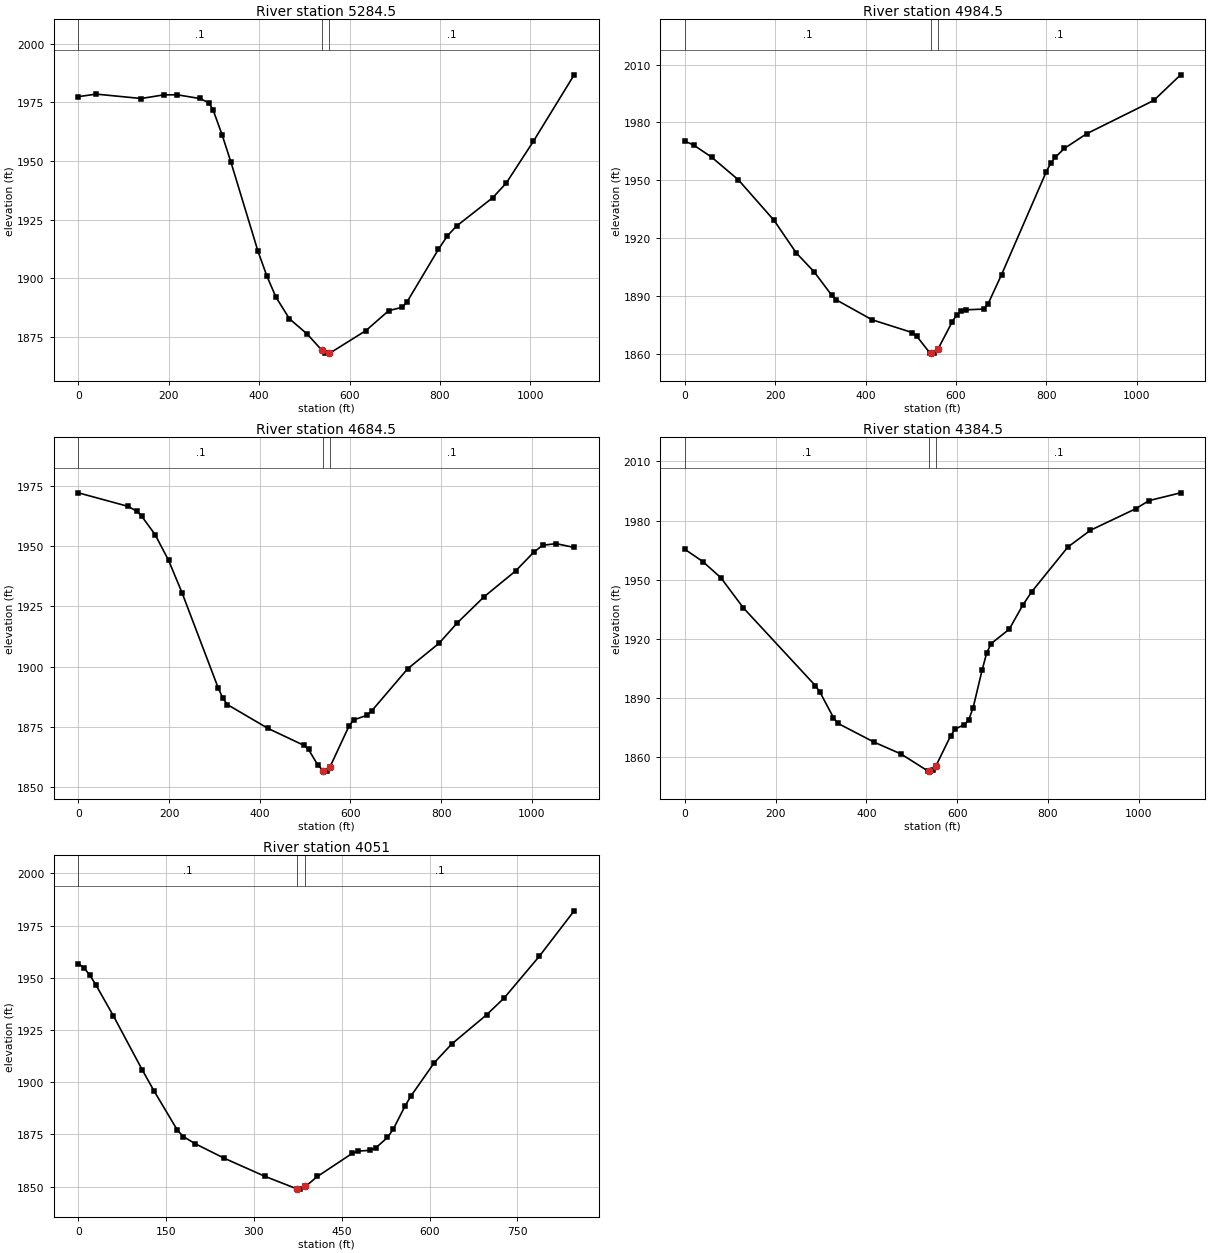
Type RM Length L Ch R = 1 ,5284.5,299.9,300,300.6
XS GIS Cut Line= 3
     1991697.353      408196.581     1992015.435      407752.478
     1992338.687      407307.080
#Sta/Elev= 30
       0 1977.48    39.7 1978.56   139.0 1976.69   188.7 1978.23   218.5 1978.28
   268.2 1976.70   288.0 1974.96   298.0 1971.83   317.8 1961.32   337.7 1949.44
   397.3 1911.62   417.2 1900.93   437.0 1892.08   466.8 1882.84   506.5 1876.26
   538.8 1869.36   546.3 1868.24   553.8 1868.20   556.3 1868.19   636.3 1877.83
   686.4 1886.28   716.4 1887.73   726.4 1889.83   796.4 1912.43   816.4 1918.20
   836.4 1922.32   916.5 1934.43   946.5 1940.68  1006.6 1958.50  1096.6 1986.78
#Mann= 3 , 0 , 0
       0     0.1       0   538.8   0.045       0   553.8     0.1       0
Bank Sta=   538.8,   553.8
Exp/Cntr=0.3,0.1

Type RM Length L Ch R = 1 ,4984.5,293.7,299.9,304.3
XS GIS Cut Line= 3
     1991953.928      408340.190     1992278.692      407893.106
     1992610.187      407460.719
#Sta/Elev= 30
       0 1970.31    19.7 1968.24    59.2 1962.00   118.4 1950.24   197.4 1929.20
   246.7 1912.26   286.2 1902.46   325.6 1890.17   335.5 1887.87   414.4 1877.57
   503.2 1870.94   513.1 1869.11   542.7 1860.25   545.1 1860.26   552.6 1860.30
   560.1 1862.23   592.2 1876.63   602.1 1880.18   612.0 1882.19   621.9 1882.71
   661.6 1883.12   671.5 1885.97   701.2 1901.06   800.2 1954.47   810.2 1958.88
   820.1 1961.93   839.9 1966.47   889.4 1974.12  1038.0 1991.41  1097.4 2004.70
#Mann= 3 , 0 , 0
       0     0.1       0   545.1   0.045       0   560.1     0.1       0
Bank Sta=   545.1,   560.1
Exp/Cntr=0.3,0.1

Type RM Length L Ch R = 1 ,4684.5,293.4,300.1,307.1
XS GIS Cut Line= 3
     1992056.214      408446.469     1992486.757      408108.533
     1992895.179      407746.522
#Sta/Elev= 30
       0 1972.03   109.5 1966.43   129.4 1964.36   139.3 1962.44   169.2 1954.73
   199.0 1944.05   228.9 1930.51   308.5 1891.14   318.4 1887.08   328.4 1884.34
   418.0 1874.46   497.6 1867.40   507.5 1865.72   527.4 1859.45   539.8 1856.87
   547.3 1856.75   554.8 1858.48   596.9 1875.48   606.9 1877.95   636.6 1879.91
   646.6 1881.66   725.9 1899.12   795.4 1909.74   835.1 1918.10   894.6 1928.98
   964.1 1939.69  1003.8 1947.38  1023.6 1950.30  1053.4 1950.99  1093.1 1949.40
#Mann= 3 , 0 , 0
       0     0.1       0   539.8   0.045       0   554.8     0.1       0
Bank Sta=   539.8,   554.8
Exp/Cntr=0.3,0.1

Type RM Length L Ch R = 1 ,4384.5,332,333.4,335.7
XS GIS Cut Line= 3
     1992115.107      408570.402     1992623.901      408372.537
     1993125.260      408155.078
#Sta/Elev= 30
       0 1965.47    39.7 1959.24    79.4 1951.05   129.0 1935.77   287.8 1896.31
   297.8 1893.02   327.6 1880.11   337.5 1877.20   416.9 1867.72   476.4 1861.70
   536.0 1853.01   538.4 1853.09   545.9 1853.33   553.4 1855.69   585.7 1870.90
   595.6 1874.33   615.5 1876.54   625.4 1878.89   635.3 1885.22   655.2 1904.38
   665.2 1912.99   675.1 1917.69   714.8 1924.94   744.6 1937.14   764.5 1943.98
   844.0 1966.61   893.7 1975.10   993.0 1985.96  1022.8 1990.14  1092.4 1994.08
#Mann= 3 , 0 , 0
       0     0.1       0   538.4   0.045       0   553.4     0.1       0
Bank Sta=   538.4,   553.4
Exp/Cntr=0.3,0.1

Type RM Length L Ch R = 1 ,4051,272.3,266.6,260.9
XS GIS Cut Line= 2
     1992339.839      408808.146     1993147.117      408551.571
#Sta/Elev= 30
       0 1956.81    10.0 1954.68    19.9 1951.14    29.9 1946.64    59.8 1931.83
   109.6 1905.68   129.6 1895.67   169.4 1876.94   179.4 1873.94   199.3 1870.56
   249.1 1863.58   318.9 1854.87     373 1848.94   378.7 1848.76     388 1850.04
   408.6 1854.84   468.4 1865.98   478.4 1866.99   498.3 1867.34   508.2 1868.53
   528.2 1873.51   538.1 1877.51   558.1 1888.53   568.0 1893.26   607.9 1909.25
   637.8 1918.25   697.6 1932.30   727.5 1940.32   787.3 1960.22   847.1 1982.09
#Mann= 3 , 0 , 0
       0     0.1       0     373   0.045       0     388     0.1       0
Bank Sta=     373,     388
Exp/Cntr=0.3,0.1