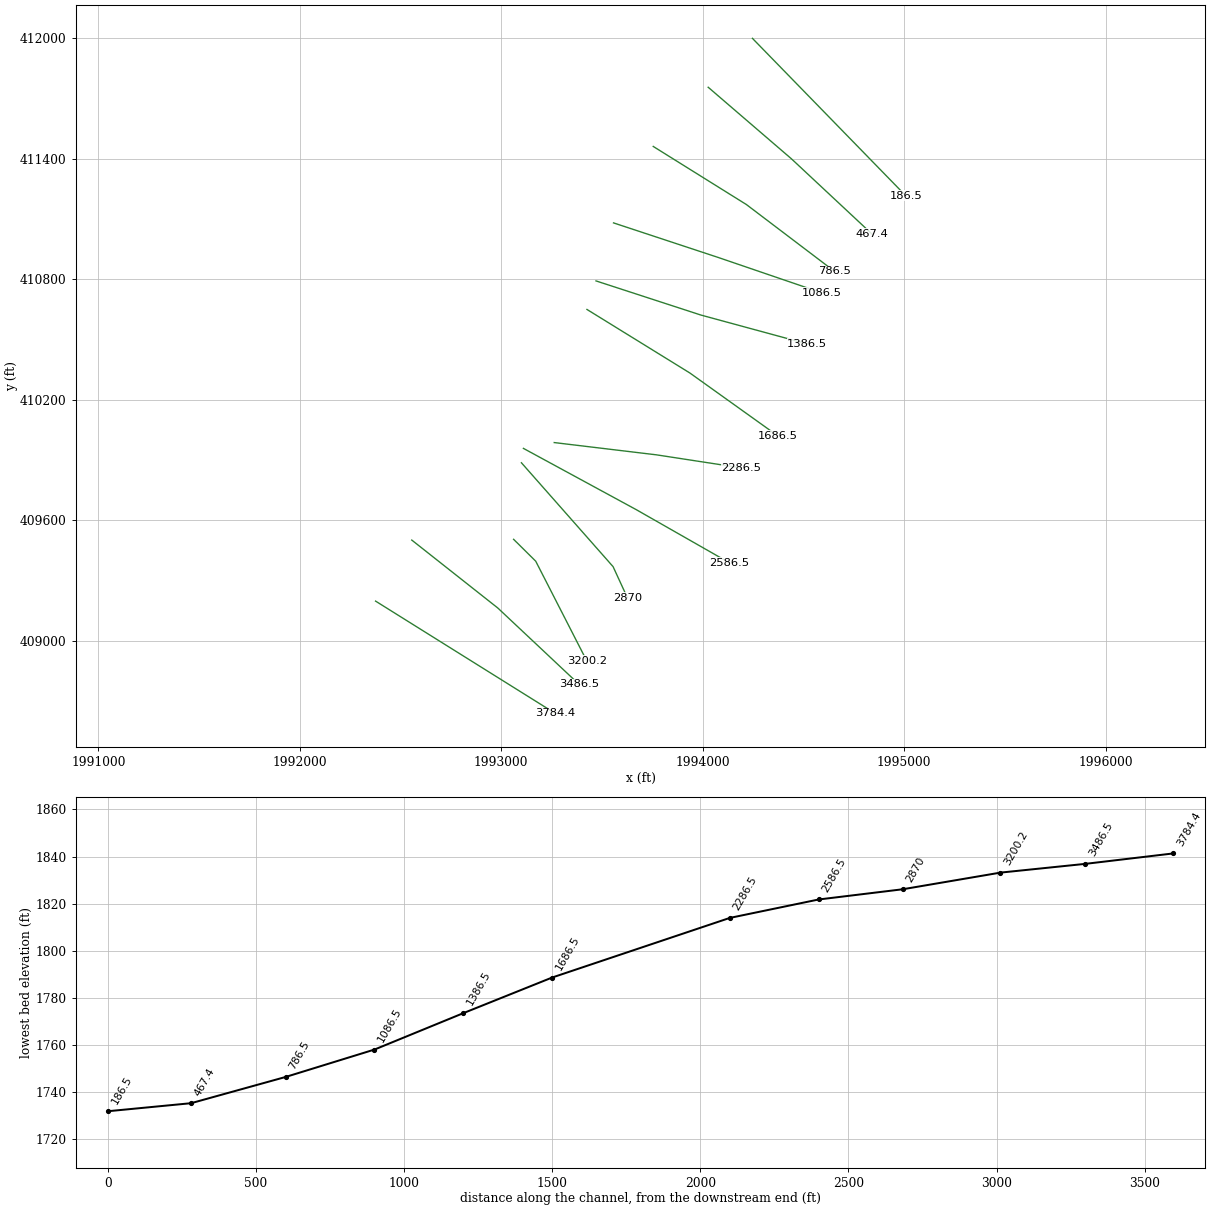
HEC-RAS study LaurelCrk4.prj: LaurelCrk4

--- LaurelCrk4.g01 (geometry) --- (continued)

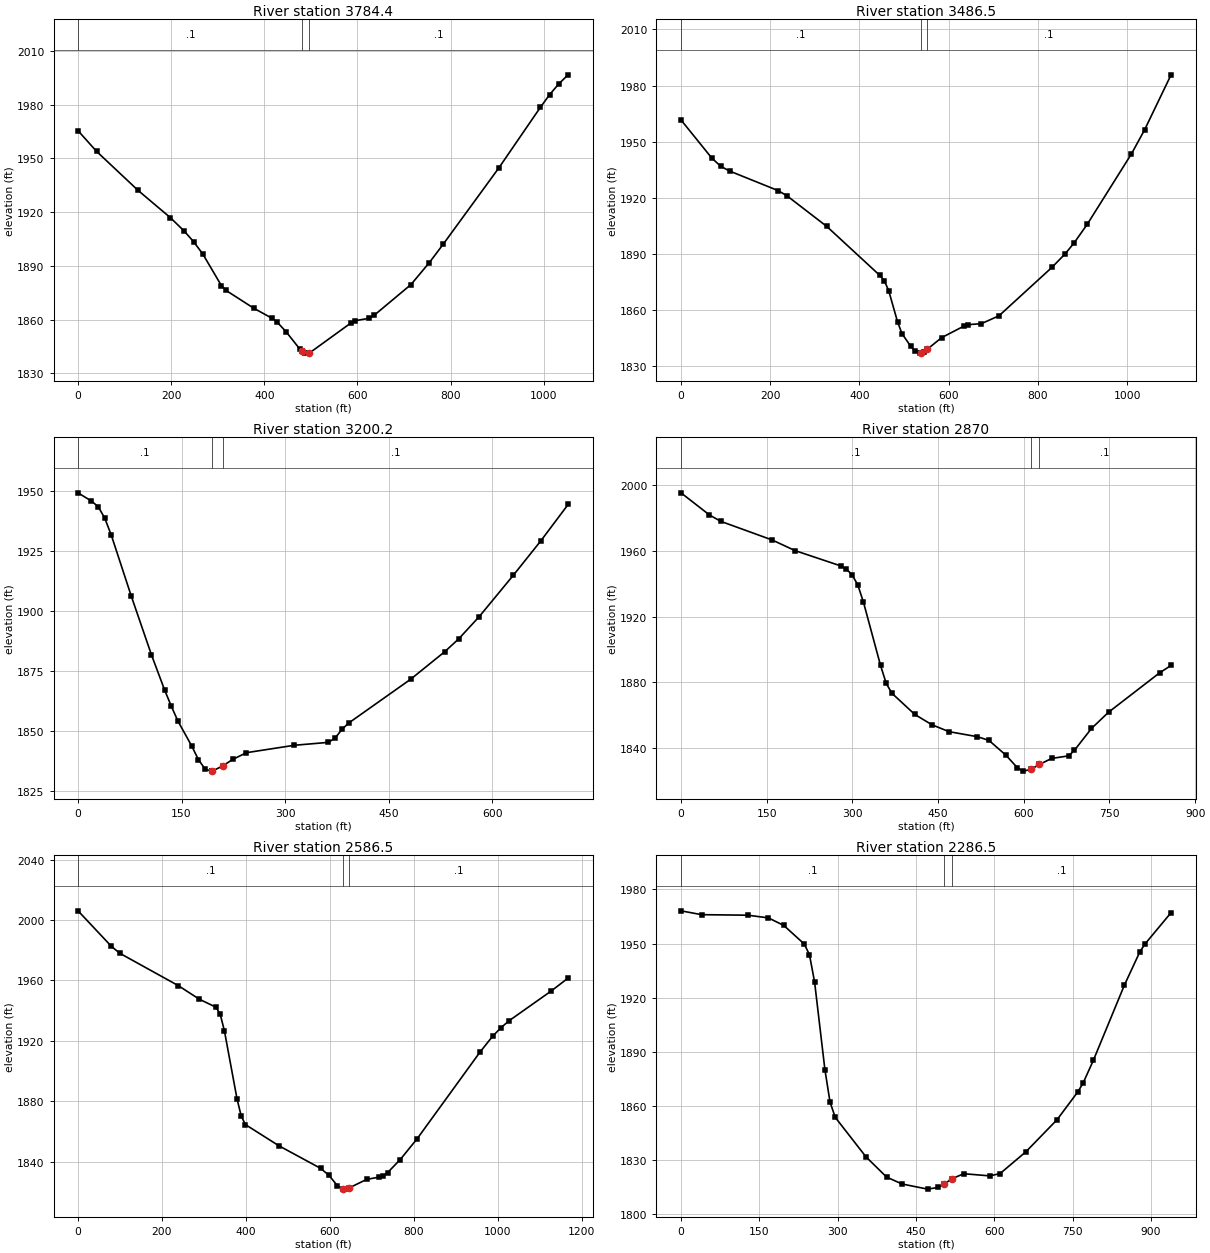
Type RM Length L Ch R = 1 ,3784.4,300.4,297.8,293.4
XS GIS Cut Line= 2
     1992376.212      409199.031     1993267.970      408640.576
#Sta/Elev= 30
       0 1965.39    39.7 1953.89   129.0 1932.07   198.5 1916.83   228.3 1909.31
   248.2 1903.44   268.0 1896.56   307.7 1879.02   317.6 1876.32   377.2 1866.38
   416.9 1860.70   426.8 1858.81   446.7 1853.24   476.5 1843.47   481.9 1842.38
   486.4 1841.47   496.3 1841.32   496.9 1841.41   585.6 1858.09   595.6 1859.44
   625.4 1860.76   635.3 1862.32   714.7 1879.55   754.4 1891.86   784.2 1902.14
   903.3 1944.58   992.6 1978.41  1012.5 1985.51  1032.3 1991.57  1052.2 1996.57
#Mann= 3 , 0 , 0
       0     0.1       0   481.9   0.045       0   496.9     0.1       0
Bank Sta=   481.9,   496.9
Exp/Cntr=0.3,0.1

Type RM Length L Ch R = 1 ,3486.5,296,286.3,278.5
XS GIS Cut Line= 3
     1992555.969      409502.560     1992983.202      409164.505
     1993386.234      408784.891
#Sta/Elev= 30
       0 1961.59    69.3 1941.13    89.2 1936.79   109.0 1934.25   217.9 1923.78
   237.7 1920.99   326.9 1904.62   445.8 1878.42   455.6 1875.70   465.6 1870.27
   485.4 1853.64   495.3 1847.34   515.1 1840.48   525.0 1837.89   534.9 1836.88
   537.3 1837.04   544.8 1837.53   552.3 1839.01   584.4 1845.19   633.8 1851.28
   643.7 1852.10   673.3 1852.64   712.9 1856.86   831.5 1882.74   861.2 1890.00
   881.0 1895.75   910.6 1905.77  1009.5 1943.34  1039.1 1956.25  1098.5 1985.71
#Mann= 3 , 0 , 0
       0     0.1       0   537.3   0.045       0   552.3     0.1       0
Bank Sta=   537.3,   552.3
Exp/Cntr=0.3,0.1

Type RM Length L Ch R = 1 ,3200.2,324.5,330.3,336.1
XS GIS Cut Line= 3
     1993061.461      409506.386     1993171.210      409397.494
     1993423.985      408902.826
#Sta/Elev= 30
       0 1949.14    19.3 1945.72    29.0 1943.43    38.6 1938.67    48.3 1931.40
    77.3 1905.96   106.3 1881.69   125.6 1866.86   135.3 1860.11   144.9 1853.92
   164.5 1843.77   174.4 1837.98   184.4 1833.91   194.3 1833.17   194.4 1833.18
   209.4 1835.31   224.0 1838.02   243.9 1840.85   313.3 1843.94   362.9 1845.16
   372.8 1847.06   382.8 1850.71   392.7 1853.32   482.0 1871.47   531.6 1883.00
   551.4 1888.23   581.2 1897.52   630.8 1914.82   670.4 1929.07   710.1 1944.28
#Mann= 3 , 0 , 0
       0     0.1       0   194.4   0.045       0   209.4     0.1       0
Bank Sta=   194.4,   209.4
Exp/Cntr=0.3,0.1

Type RM Length L Ch R = 1 ,2870,275.6,283.4,290.8
XS GIS Cut Line= 3
     1993100.105      409887.181     1993555.244      409370.344
     1993625.784      409216.666
#Sta/Elev= 30
       0 1995.14    49.9 1981.67    69.9 1977.79   159.7 1966.48   199.6 1960.05
   279.5 1950.77   289.4 1948.83   299.4 1945.38   309.4 1939.25   319.4 1928.72
   349.3 1890.27   359.3 1879.33   369.3 1873.36   409.2 1860.54   439.2 1854.27
   469.1 1850.08   519.0 1847.00   539.0 1844.78   568.9 1835.73   588.9 1828.11
   598.8 1826.10   612.2 1827.12   627.2 1830.13   648.8 1833.81   678.7 1835.38
   688.7 1838.77   718.5 1852.01   748.4 1861.88   837.9 1885.84   857.8 1890.29
#Mann= 3 , 0 , 0
       0     0.1       0   612.2   0.045       0   627.2     0.1       0
Bank Sta=   612.2,   627.2
Exp/Cntr=0.3,0.1

Type RM Length L Ch R = 1 ,2586.5,343.8,299.9,306.3
XS GIS Cut Line= 3
     1993110.089      409958.665     1993670.293      409653.869
     1994130.295      409391.010
#Sta/Elev= 30
       0 2006.16    79.7 1982.56    99.6 1978.02   239.2 1956.54   289.0 1947.59
   328.8 1942.28   338.8 1937.57   348.8 1926.53   378.7 1881.66   388.6 1870.35
   398.6 1864.57   478.3 1850.54   578.0 1835.52   597.9 1830.91   617.8 1824.07
   630.3 1821.97   637.8 1821.77   645.3 1822.49   687.7 1828.22   717.7 1829.74
   727.7 1830.71   737.7 1832.75   767.7 1841.40   807.7 1855.06   957.6 1912.54
   987.6 1923.00  1007.6 1928.72  1027.6 1933.46  1127.6 1953.09  1167.6 1961.62
#Mann= 3 , 0 , 0
       0     0.1       0   630.3   0.045       0   645.3     0.1       0
Bank Sta=   630.3,   645.3
Exp/Cntr=0.3,0.1

Type RM Length L Ch R = 1 ,2286.5,556.1,599.5,591.5
XS GIS Cut Line= 3
     1993263.005      409987.572     1993770.942      409926.476
     1994192.626      409861.607
#Sta/Elev= 30
       0 1968.13    39.4 1966.00   127.9 1965.71   167.2 1964.23   196.8 1960.03
   236.1 1949.72   246.0 1943.76   255.8 1928.63   275.5 1880.19   285.3 1862.24
   295.2 1853.75   354.2 1831.82   393.5 1820.66   423.0 1816.81   472.2 1813.95
   491.9 1814.88   504.1 1816.78   519.1 1819.75   541.4 1822.49   591.0 1821.29
   610.8 1822.55   660.4 1834.67   720.0 1852.43   759.6 1867.80   769.6 1872.59
   789.4 1885.27   849.0 1927.05   878.7 1945.56   888.6 1949.86   938.2 1967.11
#Mann= 3 , 0 , 0
       0     0.1       0   504.1   0.045       0   519.1     0.1       0
Bank Sta=   504.1,   519.1
Exp/Cntr=0.3,0.1

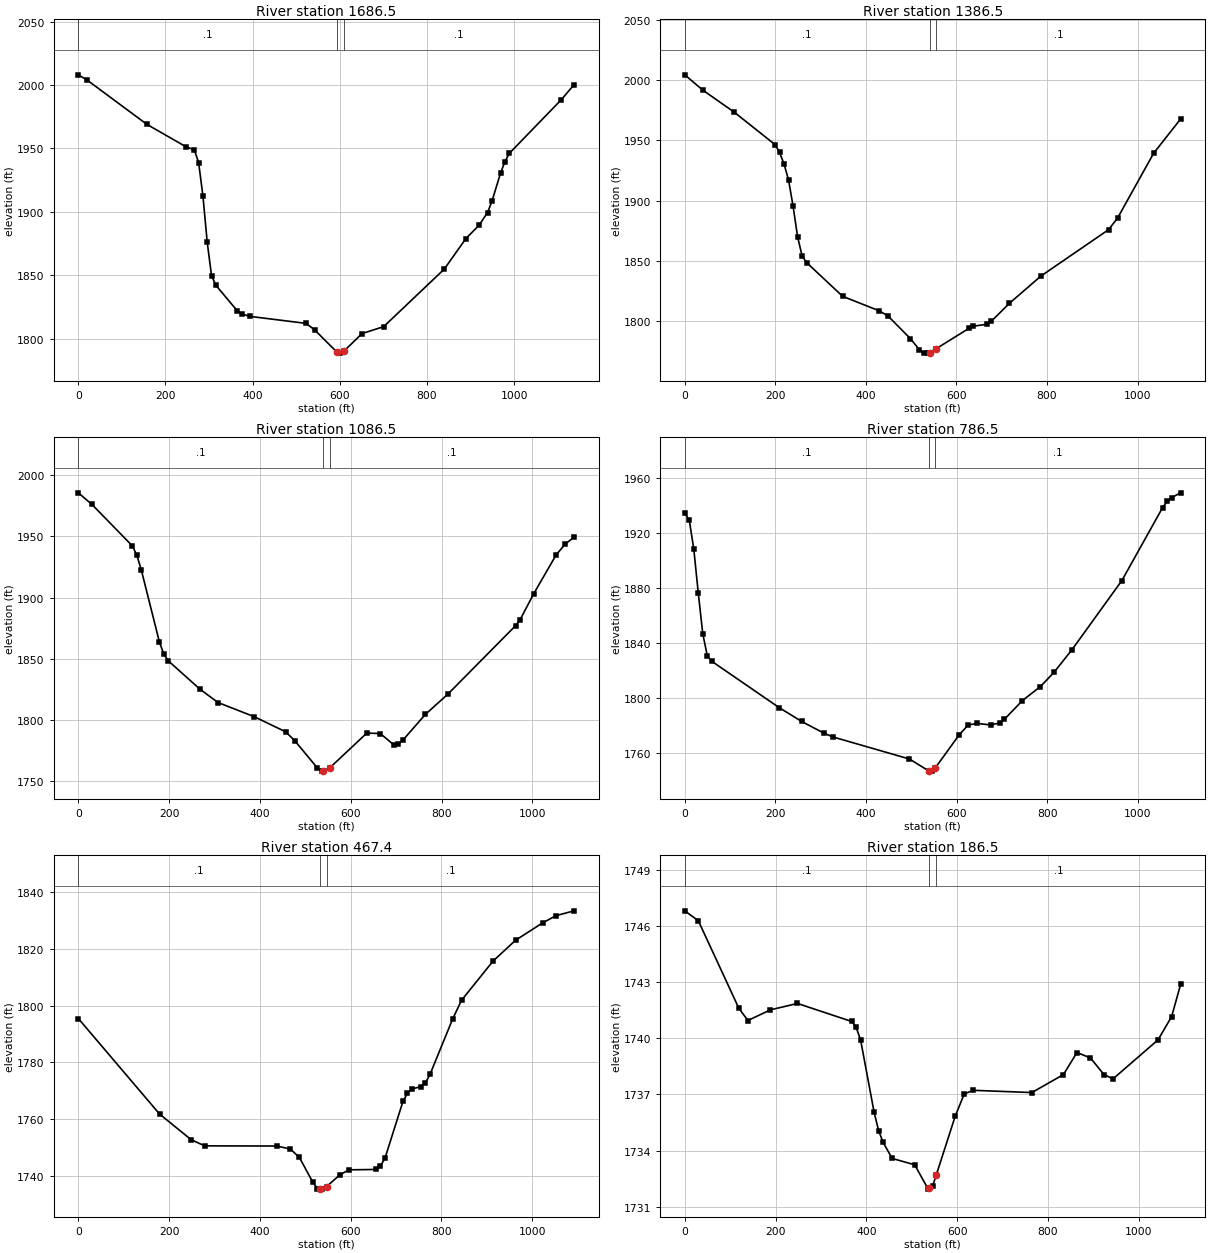
Type RM Length L Ch R = 1 ,1686.5,294.4,299.8,307.9
XS GIS Cut Line= 3
     1993425.484      410649.775     1993936.804      410333.358
     1994372.815      410020.917
#Sta/Elev= 30
       0 2008.02    19.7 2004.00   157.7 1968.90   246.4 1951.45   266.2 1948.81
   276.0 1938.88   285.9 1912.52   295.7 1876.18   305.6 1849.81   315.4 1842.25
   364.7 1822.01   374.6 1819.54   394.3 1817.60   522.4 1812.12   542.2 1807.00
   593.8 1789.29   601.3 1788.67   608.8 1790.02   651.0 1804.11   700.6 1809.53
   839.7 1854.91   889.4 1879.01   919.2 1889.34   939.0 1899.48   949.0 1908.31
   968.8 1930.57   978.8 1939.55   988.7 1946.04  1107.9 1988.30  1137.7 2000.34
#Mann= 3 , 0 , 0
       0     0.1       0   593.8   0.045       0   608.8     0.1       0
Bank Sta=   593.8,   608.8
Exp/Cntr=0.3,0.1

Type RM Length L Ch R = 1 ,1386.5,300.1,300,298.6
XS GIS Cut Line= 3
     1993470.374      410791.693     1993991.381      410621.784
     1994519.312      410478.108
#Sta/Elev= 30
       0 2004.40    39.9 1991.67   109.6 1973.30   199.3 1946.51   209.2 1940.10
   219.2 1930.46   229.2 1917.04   239.1 1895.58   249.1 1870.08   259.1 1854.18
   269.0 1848.67   348.7 1820.65   428.4 1808.81   448.4 1804.53   498.2 1785.60
   518.1 1776.44   528.1 1773.66   538.0 1773.56   540.5 1774.01   555.5 1777.30
   627.6 1794.11   637.5 1795.89   667.4 1797.53   677.3 1800.08   717.1 1814.94
   786.8 1837.56   936.0 1875.97   955.9 1885.64  1035.5 1939.33  1095.1 1967.80
#Mann= 3 , 0 , 0
       0     0.1       0   540.5   0.045       0   555.5     0.1       0
Bank Sta=   540.5,   555.5
Exp/Cntr=0.3,0.1

Type RM Length L Ch R = 1 ,1086.5,305.4,300,292.8
XS GIS Cut Line= 3
     1993557.287      411080.290     1994075.654      410908.815
     1994592.295      410731.981
#Sta/Elev= 30
       0 1985.60    29.8 1976.15   119.1 1942.18   129.0 1934.41   139.0 1922.15
   178.7 1863.47   188.6 1853.47   198.5 1848.15   268.0 1825.05   307.7 1814.18
   387.2 1802.64   456.6 1790.26   476.5 1783.09   526.1 1760.88   536.1 1758.11
   538.5 1758.17   553.5 1760.69   635.4 1789.21   665.1 1788.83   694.9 1779.61
   704.8 1780.14   714.8 1783.41   764.4 1804.50   814.1 1821.10   963.0 1876.99
   972.9 1881.81  1002.7 1902.91  1052.3 1934.79  1072.2 1943.64  1092.1 1949.43
#Mann= 3 , 0 , 0
       0     0.1       0   538.5   0.045       0   553.5     0.1       0
Bank Sta=   538.5,   553.5
Exp/Cntr=0.3,0.1

Type RM Length L Ch R = 1 ,786.5,322.6,319.2,317.1
XS GIS Cut Line= 3
     1993754.600      411460.480     1994217.193      411171.359
     1994654.115      410839.326
#Sta/Elev= 30
       0 1934.37     9.9 1929.24    19.8 1908.31    29.8 1876.00    39.7 1846.52
    49.6 1830.49    59.5 1826.48   208.3 1792.72   257.9 1782.65   307.5 1774.05
   327.3 1771.33   495.9 1755.29     538 1746.72   545.5 1746.48     553 1748.91
   605.4 1772.82   625.3 1780.07   645.3 1781.25   675.2 1780.08   695.2 1781.62
   705.2 1784.15   745.1 1797.86   785.0 1808.10   814.9 1818.43   854.8 1835.04
   964.6 1885.24  1054.4 1938.31  1064.4 1942.86  1074.3 1945.67  1094.3 1949.15
#Mann= 3 , 0 , 0
       0     0.1       0     538   0.045       0     553     0.1       0
Bank Sta=     538,     553
Exp/Cntr=0.3,0.1

Type RM Length L Ch R = 1 ,467.4,282.8,280.8,279.5
XS GIS Cut Line= 3
     1994027.253      411754.979     1994441.355      411398.251
     1994839.874      411025.170
#Sta/Elev= 30
       0 1795.48   178.9 1761.83   248.4 1752.79   278.2 1750.60   437.2 1750.54
   467.1 1749.49   486.9 1746.56   516.8 1737.76   526.7 1735.50   532.1 1735.42
   536.6 1735.35   547.1 1736.24   576.3 1740.41   596.2 1742.15   655.8 1742.28
   665.7 1743.52   675.6 1746.22   715.3 1766.28   725.2 1769.14   735.2 1770.63
   755.0 1771.51   764.9 1772.87   774.8 1775.76   824.5 1795.22   844.3 1801.90
   913.8 1815.73   963.4 1823.07  1023.0 1829.19  1052.8 1831.75  1092.5 1833.44
#Mann= 3 , 0 , 0
       0     0.1       0   532.1   0.045       0   547.1     0.1       0
Bank Sta=   532.1,   547.1
Exp/Cntr=0.3,0.1

Type RM Length L Ch R = 1 ,186.5,188.4,186.5,184.6
XS GIS Cut Line= 3
     1994246.789      411998.259     1994627.392      411606.779
     1995007.996      411215.298
#Sta/Elev= 30
       0 1746.81    29.8 1746.28   119.1 1741.60   139.0 1740.95   188.6 1741.52
   248.2 1741.86   367.3 1740.90   377.2 1740.60   387.2 1739.91   417.0 1736.04
   426.9 1735.06   436.8 1734.44   456.6 1733.58   506.3 1733.24   536.1 1731.94
   538.5 1731.98   546.0 1732.12   553.5 1732.67   595.6 1735.84   615.5 1737.03
   635.4 1737.22   764.4 1737.10   833.9 1738.06   863.7 1739.24   893.4 1738.95
   923.2 1738.06   943.1 1737.83  1042.4 1739.92  1072.2 1741.16  1092.0 1742.88
#Mann= 3 , 0 , 0
       0     0.1       0   538.5   0.045       0   553.5     0.1       0
Bank Sta=   538.5,   553.5
Exp/Cntr=0.3,0.1